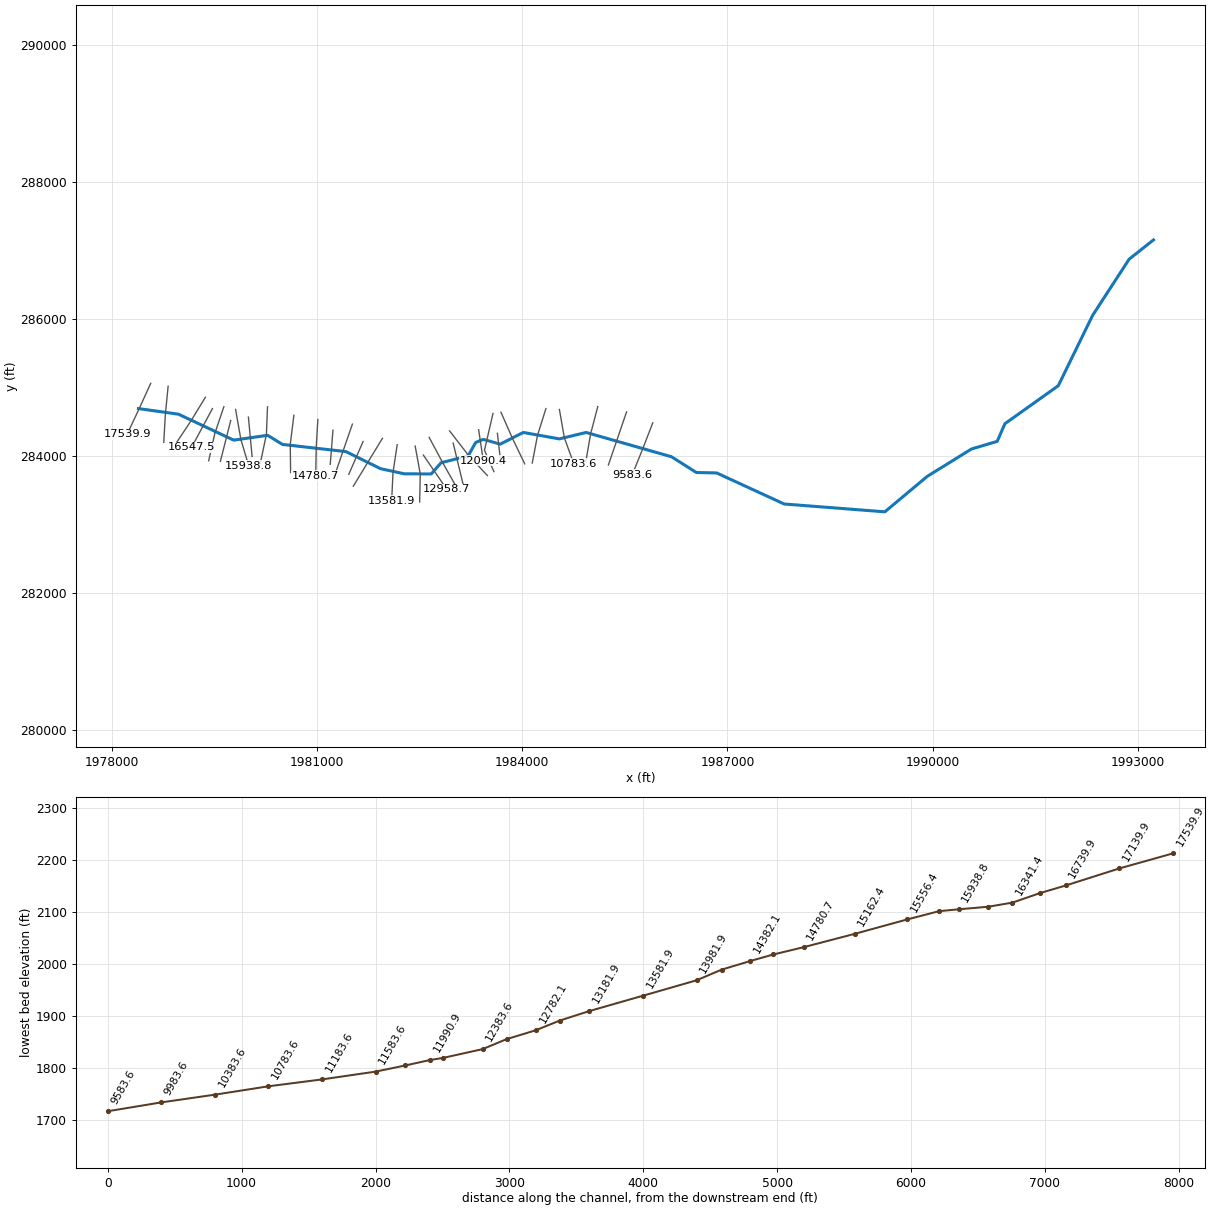
--- FrlyBrnch.prj (project) ---

Proj Title=FrlyBrnch
Current Plan=p01
Default Exp/Contr=0,0
English Units
Geom File=g01
Flow File=f01
Plan File=p01
BEGIN DESCRIPTION:
END DESCRIPTION:
DSS Export Rating Curves= 0
DSS Export Rating Curve Sorted= 0
DSS Export Volume Flow Curves= 0
DXF OffsetX= 0
DXF OffsetY= 0
DXF ScaleX= 0
DXF ScaleY= 0

--- FrlyBrnch.p01 (plan) ---

Plan Title=Floodplain
Program Version=4.00
Geom File=g01
Flow File=f01
K Sum by GR=0
Std Step Tol=0.01
Critical Tol=0.01
Num of Std Step Trials=20
Max Error Tol=0.3
Flow Tol Ratio=0.001
Split Flow NTrial=30
Split Flow Tol=0.02
Split Flow Ratio=0.02
Log Output Level=0
Friction Slope Method=1
Unsteady Friction Slope Method=2
Unsteady Bridges Friction Slope Method=1
Global Log Level=0
CheckData=False
Run HTab=0
Run UNet=0
Run PostProcess=0
UNET Theta=0
UNET Theta Warmup=0
UNET ZTol=0
UNET ZSATol=0
UNET MxIter=0
UNET MaxInSteps=0
UNET DtIC=0
UNET DtMin=0
UNET MaxCRTS=0
UNET WFStab=0
UNET SFStab=0
UNET WFX=0
UNET SFX=0
UNET DSS MLevel=0
UNET DZMax Abort=0
UNET Convert EG Bridges=0
UNET Use Existing IB Tables=0
UNET Froude Limit=0
UNET Froude Power=0
Write IC File=0
Echo Input=False
Echo Output=False
Write Detailed=0

--- FrlyBrnch.f01 (steady flow) ---

Flow Title=NFF Regression Equation
Program Version=4.00
Number of Profiles=1
Profile Names=P100yr
River Rch & RM=FrlyBrnch,Main      ,17539.9
541.7827
River Rch & RM=FrlyBrnch,Main      ,16547.5
545.8678
River Rch & RM=FrlyBrnch,Main      ,16341.4
665.2071
River Rch & RM=FrlyBrnch,Main      ,12958.7
720.9590
River Rch & RM=FrlyBrnch,Main      ,12782.1
836.7404
River Rch & RM=FrlyBrnch,Main      ,11805.8
853.2057
River Rch & RM=FrlyBrnch,Main      ,10383.6
946.8564
River Rch & RM=FrlyBrnch,Main      ,7583.6
1026.061
River Rch & RM=FrlyBrnch,Main      ,5583.6
1260.231
River Rch & RM=FrlyBrnch,Main      ,5583.6
1129.359
River Rch & RM=FrlyBrnch,Main      ,725.5
1343.976
Boundary for River Rch & Prof#=FrlyBrnch,Main      ,1
Up Type=0
Dn Type=3
Dn Slope=0.027431

--- FrlyBrnch.g01 (geometry) ---

Geom Title=USGS 3m DEM
Program Version=4.10

River Reach=FrlyBrnch       ,Main
Reach XY= 30
     1978393.311      284694.662     1978977.946      284612.631
     1979785.238      284233.724     1980281.253      284304.417
     1980497.478      284171.224     1981426.358      284066.105
     1981929.769      283817.058      1982280.03      283741.537
     1982671.957      283740.235     1982814.618      283903.408
     1983211.019      284004.558      1983321.01      284200.023
     1983434.304      284244.879     1983678.467      284175.131
     1984017.009      284345.704      1984543.05      284251.953
     1984934.978      284345.704     1986181.071      283991.537
     1986545.655      283761.068      1986842.53      283754.558
     1987828.207      283301.433     1989299.561      283186.849
     1989918.051      283703.776      1990565.33      284104.447
     1990941.106      284215.723     1991053.467      284473.308
     1991833.415      285027.995     1992336.019      286056.641
      1992869.39      286876.401     1993225.557      287157.998

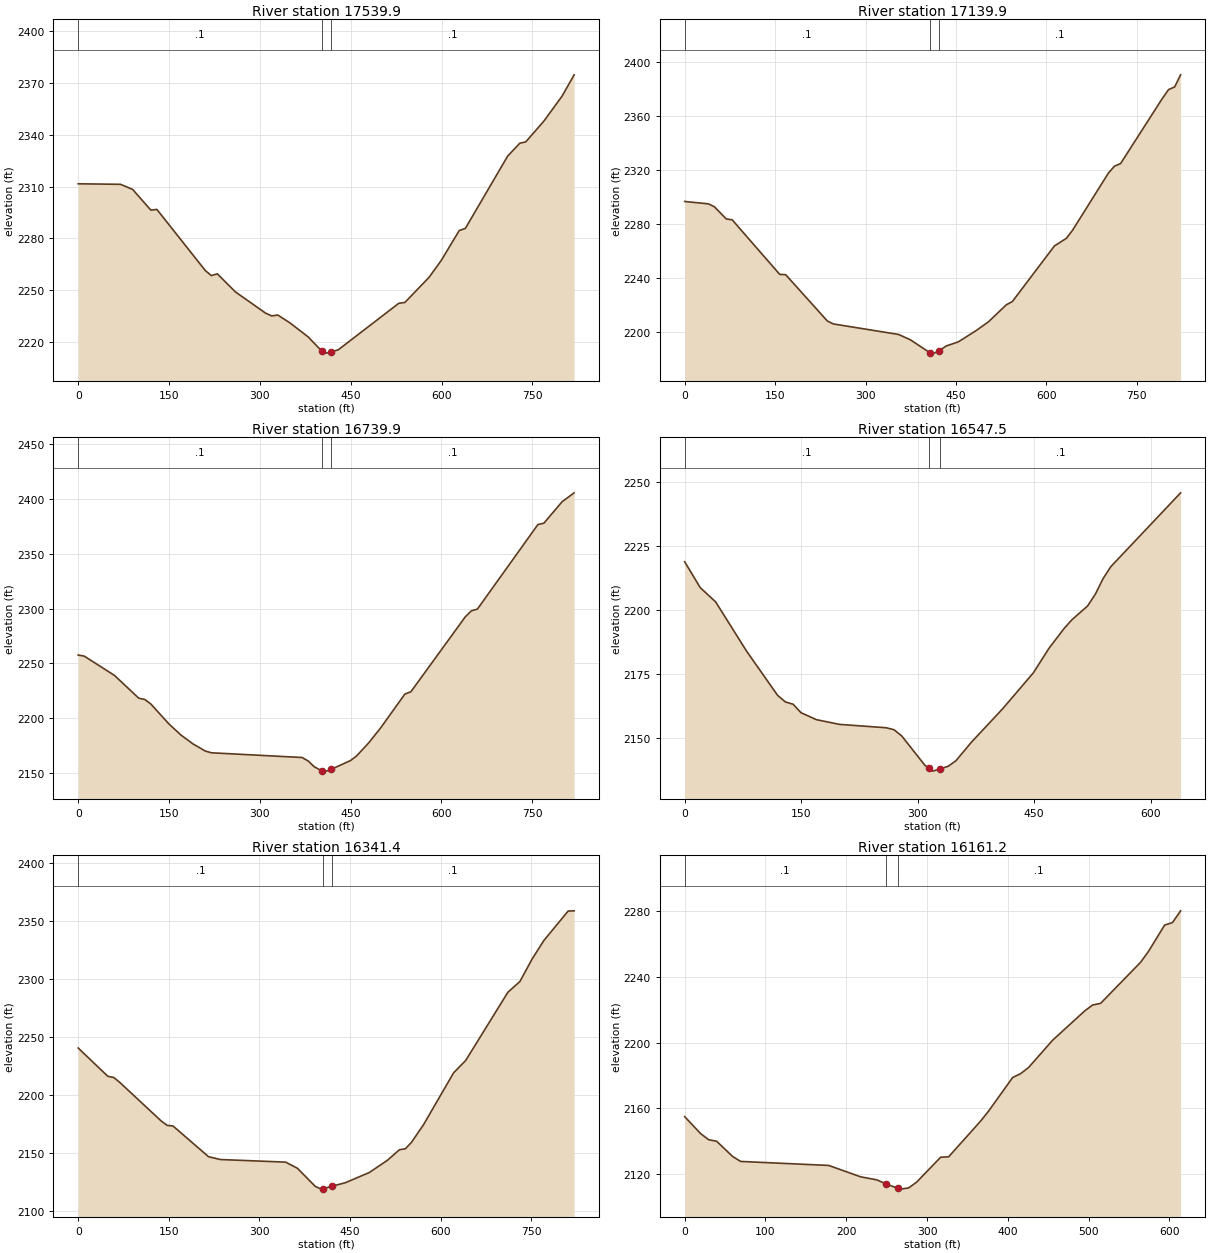
Type RM Length L Ch R = 1 ,17539.9 ,392.6,400.1,408.7
XS GIS Cut Line= 3
     1978572.328      285062.997     1978402.354      284690.392
     1978227.497      284320.109
#Sta/Elev= 30
       0 2311.58    69.9 2311.29    89.9 2308.33   119.9 2296.32   129.9 2296.74
   209.8 2261.33   219.8 2258.34   229.7 2259.38   259.7 2248.87   309.6 2236.54
   319.6 2234.98   329.6 2235.48   349.6 2230.95   379.6 2222.84     402 2214.66
   409.5 2213.39     417 2213.98   429.5 2215.33   529.4 2242.28   539.4 2242.76
   579.3 2257.32   599.3    2267   629.3 2284.52   639.3 2285.69   709.2 2327.65
   729.2  2335.1   739.1  2335.9   769.1 2347.98   799.1 2362.46     819 2374.78
#Mann= 3 , 0 , 0
       0      .1       0     402    .045       0     417      .1       0
Bank Sta=402,417
XS Rating Curve= 0 ,0
Exp/Cntr=0.3,0.1

Type RM Length L Ch R = 1 ,17139.9 ,410,399.7,387.6
XS GIS Cut Line= 3
     1978826.809      285021.267     1978786.384      284609.329
     1978763.065      284201.274
#Sta/Elev= 30
       0 2296.56    39.4  2294.8    49.3 2292.62      69 2283.64    78.8 2282.99
   157.7 2242.63   167.5 2242.43   236.5 2208.23   246.4    2206   354.8  2198.2
   374.5 2194.23   406.4 2184.79   413.9  2184.4   421.4 2185.94   433.8 2189.69
   453.8 2192.71   483.7 2201.15   503.6 2207.46   533.5 2220.15   543.5 2222.54
   613.3 2263.66   633.2 2269.35   643.2 2275.17     703 2317.65     713  2322.7
     723 2324.56   792.7 2373.02   802.7 2379.33   812.7 2381.27   822.6 2390.22
#Mann= 3 , 0 , 0
       0      .1       0   406.4    .045       0   421.4      .1       0
Bank Sta=406.4,421.4
XS Rating Curve= 0 ,0
Exp/Cntr=0.3,0.1

Type RM Length L Ch R = 1 ,16739.9 ,191,192.3,194.4
XS GIS Cut Line= 3
     1979371.437       284860.11     1979157.967      284510.219
     1978930.456      284169.717
#Sta/Elev= 30
       0 2257.64      10 2256.64      60 2238.98     100 2218.24     110 2217.03
     120  2212.9     150 2194.61     170 2184.44   189.9 2176.35   209.9 2169.97
   219.9 2168.33   369.9 2164.03   379.9 2160.89   389.9 2155.62   402.4 2151.84
   409.9 2151.58   417.4 2153.08   449.8  2161.2   459.8 2165.38   479.8 2177.28
   499.8 2191.15   539.7 2221.96   549.7  2224.1   639.6 2292.58   649.6 2298.01
   659.6 2299.63   759.5 2376.82   769.4 2378.07   799.4 2397.62   819.4 2405.81
#Mann= 3 , 0 , 0
       0      .1       0   402.4    .045       0   417.4      .1       0
Bank Sta=402.4,417.4
XS Rating Curve= 0 ,0
Exp/Cntr=0.3,0.1

Type RM Length L Ch R = 1 ,16547.5 ,202.5,206.1,212
XS GIS Cut Line= 2
     1979474.437      284694.817     1979171.963      284132.471
#Sta/Elev= 30
       0  2218.8      20 2208.69    39.9 2203.09    79.8 2183.79   119.7 2166.52
   129.7 2163.96   139.7 2163.05   149.7 2159.76   169.6 2157.03   199.5 2155.18
   259.4 2153.87   269.4 2153.11   279.4 2150.68   309.3 2139.18   314.1 2138.09
   319.3  2136.9   329.1 2137.81   339.2 2138.78   349.2 2140.96   369.2 2148.23
   409.1  2161.2     449 2175.38   468.9  2184.9   488.9 2192.85   498.8 2196.18
   518.8 2201.52   528.8 2206.16   538.8 2212.28   548.7  2216.9   638.5 2245.76
#Mann= 3 , 0 , 0
       0      .1       0   314.1    .045       0   329.1      .1       0
Bank Sta=314.1,329.1
XS Rating Curve= 0 ,0
Exp/Cntr=0.3,0.1

Type RM Length L Ch R = 1 ,16341.4 ,178.3,180.1,179.5
XS GIS Cut Line= 3
     1979641.372      284721.491     1979509.097      284331.278
     1979419.545      283932.083
#Sta/Elev= 30
       0 2240.37      49    2216    58.9 2214.93    68.7 2210.75   137.3 2177.44
   147.2 2173.63     157 2173.04   215.8 2146.55   235.4 2144.11   343.4 2141.85
     363 2136.52   392.4 2120.96   402.2 2118.55   404.5 2118.74   419.5 2120.98
     442 2124.02   481.9 2132.87   511.8  2143.4   531.8 2152.54   541.7 2153.42
   551.7  2158.9   571.7 2174.16   621.6 2219.02   641.5  2229.6   711.4 2288.52
   731.3  2297.8   751.3 2317.06   771.2 2333.36   811.2 2358.66   821.1 2358.83
#Mann= 3 , 0 , 0
       0      .1       0   404.5    .045       0   419.5      .1       0
Bank Sta=404.5,419.5
XS Rating Curve= 0 ,0
Exp/Cntr=0.3,0.1

Type RM Length L Ch R = 1 ,16161.2 ,211.4,222.5,234.7
XS GIS Cut Line= 2
     1979741.409      284520.149     1979590.882      283925.142
#Sta/Elev= 30
       0 2154.81    19.8 2144.44    29.7 2140.74    39.6 2139.79    59.4 2130.51
    69.3 2127.49   178.2 2125.05   217.8  2118.1   237.6 2116.28   248.8 2113.91
   263.8 2111.08   267.3  2110.6   277.2 2111.33   287.1 2114.88   316.8 2130.06
   326.7 2130.31   366.3 2152.12   376.2 2158.23   405.9 2178.66   415.8 2181.04
   425.7 2184.81   455.4 2201.43     495 2219.25   504.9  2222.9   514.8 2223.91
   564.3 2248.98   574.2 2255.72     594 2271.64   603.8 2273.22   613.8 2280.34
#Mann= 3 , 0 , 0
       0      .1       0   248.8    .045       0   263.8      .1       0
Bank Sta=248.8,263.8
XS Rating Curve= 0 ,0
Exp/Cntr=0.3,0.1

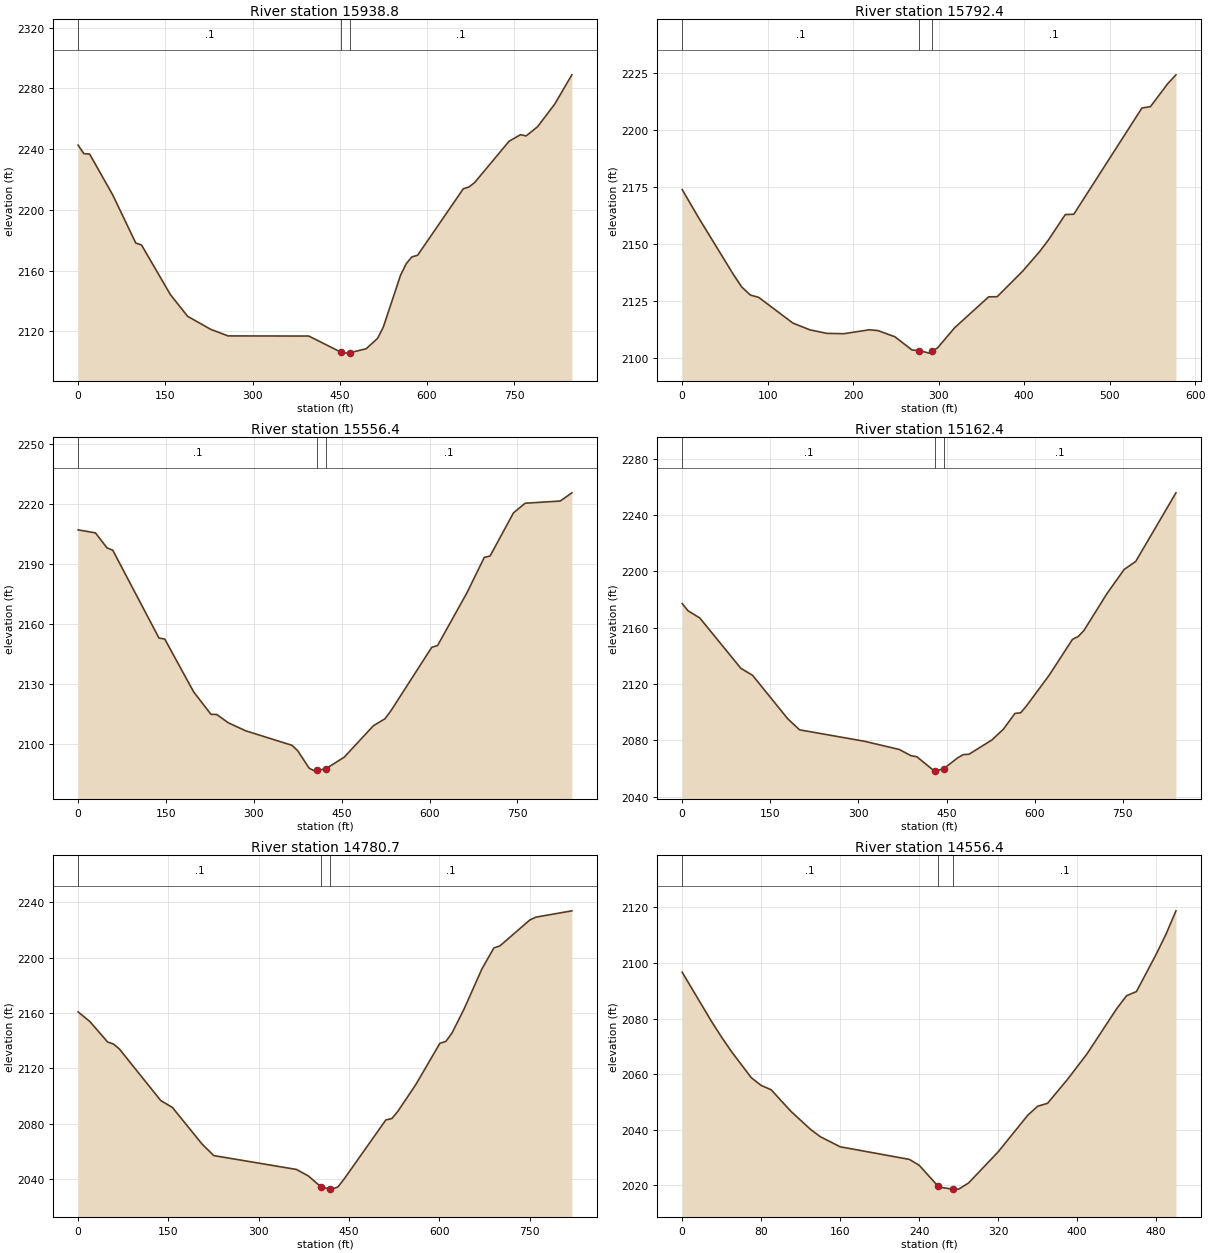
Type RM Length L Ch R = 1 ,15938.8 ,149.7,146.3,141.8
XS GIS Cut Line= 3
     1979812.547      284682.862     1979889.964      284243.287
     1980004.808      283856.998
#Sta/Elev= 30
       0 2242.63     9.9 2237.02    19.8 2236.74    59.5 2209.88    99.2 2178.13
   109.1 2176.84   158.7  2144.2   188.4 2129.86   228.1  2121.3   257.9 2116.97
   396.8 2116.88   452.2 2106.23   456.2 2105.63   467.2 2105.88   495.5 2108.51
   515.2 2115.41     525 2122.79   554.5 2156.81   564.3 2164.47   574.1 2169.01
     584  2170.1   662.6 2213.91   672.4 2215.07   682.2 2218.01   741.2 2245.14
   760.9 2249.49   770.7  2248.7   790.4 2254.77   819.8 2269.64   849.3 2288.92
#Mann= 3 , 0 , 0
       0      .1       0   452.2    .045       0   467.2      .1       0
Bank Sta=452.2,467.2
XS Rating Curve= 0 ,0
Exp/Cntr=0.3,0.1

Type RM Length L Ch R = 1 ,15792.4 ,241,236,229.2
XS GIS Cut Line= 2
     1979999.861      284569.851     1980053.823      283994.725
#Sta/Elev= 30
       0 2173.83    19.9 2161.03    59.8 2136.59    69.7 2131.02    79.7 2127.49
    89.6 2126.45   129.5 2115.18   149.4  2112.2   169.3 2110.65   189.2 2110.51
   219.1 2112.23   229.1 2111.86     249 2109.13   268.9 2103.33   277.2 2103.12
   288.8 2101.97   292.2 2102.76   298.8 2104.29   318.7 2113.12   358.5  2126.7
   368.5 2126.77   398.4 2138.02   418.3 2146.66   428.3 2151.62   448.2 2162.86
   458.1 2162.98   537.8 2209.66   547.8 2210.27   567.7 2220.23   577.6 2224.24
#Mann= 3 , 0 , 0
       0      .1       0   277.2    .045       0   292.2      .1       0
Bank Sta=277.2,292.2
XS Rating Curve= 0 ,0
Exp/Cntr=0.3,0.1

Type RM Length L Ch R = 1 ,15556.4 ,392.7,393.9,399
XS GIS Cut Line= 3
     1980279.048      284720.731      1980262.89      284316.702
     1980172.073      283887.537
#Sta/Elev= 30
       0 2206.85    29.6 2205.34    49.3 2197.86    59.2 2196.65   138.1 2152.74
   147.9 2152.26   197.2 2125.86   226.8 2114.61   236.7 2114.53   256.4 2110.37
     286 2106.37   364.9 2099.12   374.8 2096.46   394.5 2087.66   404.4 2086.19
   408.5 2086.51   423.5 2087.48   454.2 2093.14     504 2108.85     524 2112.39
     534 2116.34   603.8 2148.12   613.7    2149   663.6 2175.22   693.5 2193.09
   703.4 2193.79   743.3 2215.36   763.3 2220.17   823.1 2221.26     843 2225.37
#Mann= 3 , 0 , 0
       0      .1       0   408.5    .045       0   423.5      .1       0
Bank Sta=408.5,423.5
XS Rating Curve= 0 ,0
Exp/Cntr=0.3,0.1

Type RM Length L Ch R = 1 ,15162.4 ,381.2,381.7,381.1
XS GIS Cut Line= 3
     1980664.621       284597.08     1980611.191      284171.072
      1980616.65      283760.149
#Sta/Elev= 30
       0 2177.16      10 2172.02      30 2166.92    99.8 2131.23   119.8 2126.24
   179.7 2095.39   199.7 2087.58   309.5 2079.51   369.4 2073.64   389.4 2069.22
   399.4 2068.45   429.4 2058.27   429.9 2058.27   444.9 2059.91   468.5  2067.6
   478.3 2069.98     488 2070.22   527.2  2080.4   546.8  2088.1   566.3 2099.21
   576.1 2099.68   585.9  2104.5     625 2126.56   664.2 2151.74     674 2153.79
   683.8 2158.11   722.9 2184.22   752.2 2201.36   771.8    2207   840.3 2255.71
#Mann= 3 , 0 , 0
       0      .1       0   429.9    .045       0   444.9      .1       0
Bank Sta=429.9,444.9
XS Rating Curve= 0 ,0
Exp/Cntr=0.3,0.1

Type RM Length L Ch R = 1 ,14780.7 ,224.8,224.3,222.9
XS GIS Cut Line= 3
     1981014.467      284535.359     1980990.506      284124.459
     1980983.617      283715.818
#Sta/Elev= 30
       0 2160.82    19.6 2153.81      49 2139.02    58.8 2137.52    68.6 2133.96
   137.2 2096.69   156.8 2091.58   205.8 2065.22   225.4  2056.8   362.6 2046.78
   382.2 2042.16   404.1 2033.93   419.1 2032.56   421.6 2032.52   431.5 2034.07
   441.5 2039.55   511.3 2082.62   521.2 2083.59   531.2 2088.83   561.1 2108.23
     601 2138.04     611 2139.46   620.9 2145.33   640.9 2162.59   670.8 2191.83
   690.7  2207.1   700.7 2208.56   750.5 2227.35   760.5 2229.37   820.3 2233.96
#Mann= 3 , 0 , 0
       0      .1       0   404.1    .045       0   419.1      .1       0
Bank Sta=404.1,419.1
XS Rating Curve= 0 ,0
Exp/Cntr=0.3,0.1

Type RM Length L Ch R = 1 ,14556.4 ,180,174.3,168.6
XS GIS Cut Line= 2
     1981235.317      284379.563     1981195.555       283881.12
#Sta/Elev= 30
       0 2096.69      30 2078.82      40 2073.29      50  2068.1      70 2058.73
      80 2055.94      90 2054.42     110 2046.67     130 2040.12     140 2037.47
     160 2033.86     230 2029.33     240 2027.22   258.8 2019.79     260 2019.35
   273.8 2018.63     280 2018.62     290 2020.83     320 2032.05     350 2045.24
     360 2048.46     370 2049.52     390 2058.04     410 2067.34     440 2083.58
     450 2088.24     460 2089.74     480 2103.17     490 2110.44     500  2118.8
#Mann= 3 , 0 , 0
       0      .1       0   258.8    .045       0   273.8      .1       0
Bank Sta=258.8,273.8
XS Rating Curve= 0 ,0
Exp/Cntr=0.3,0.1

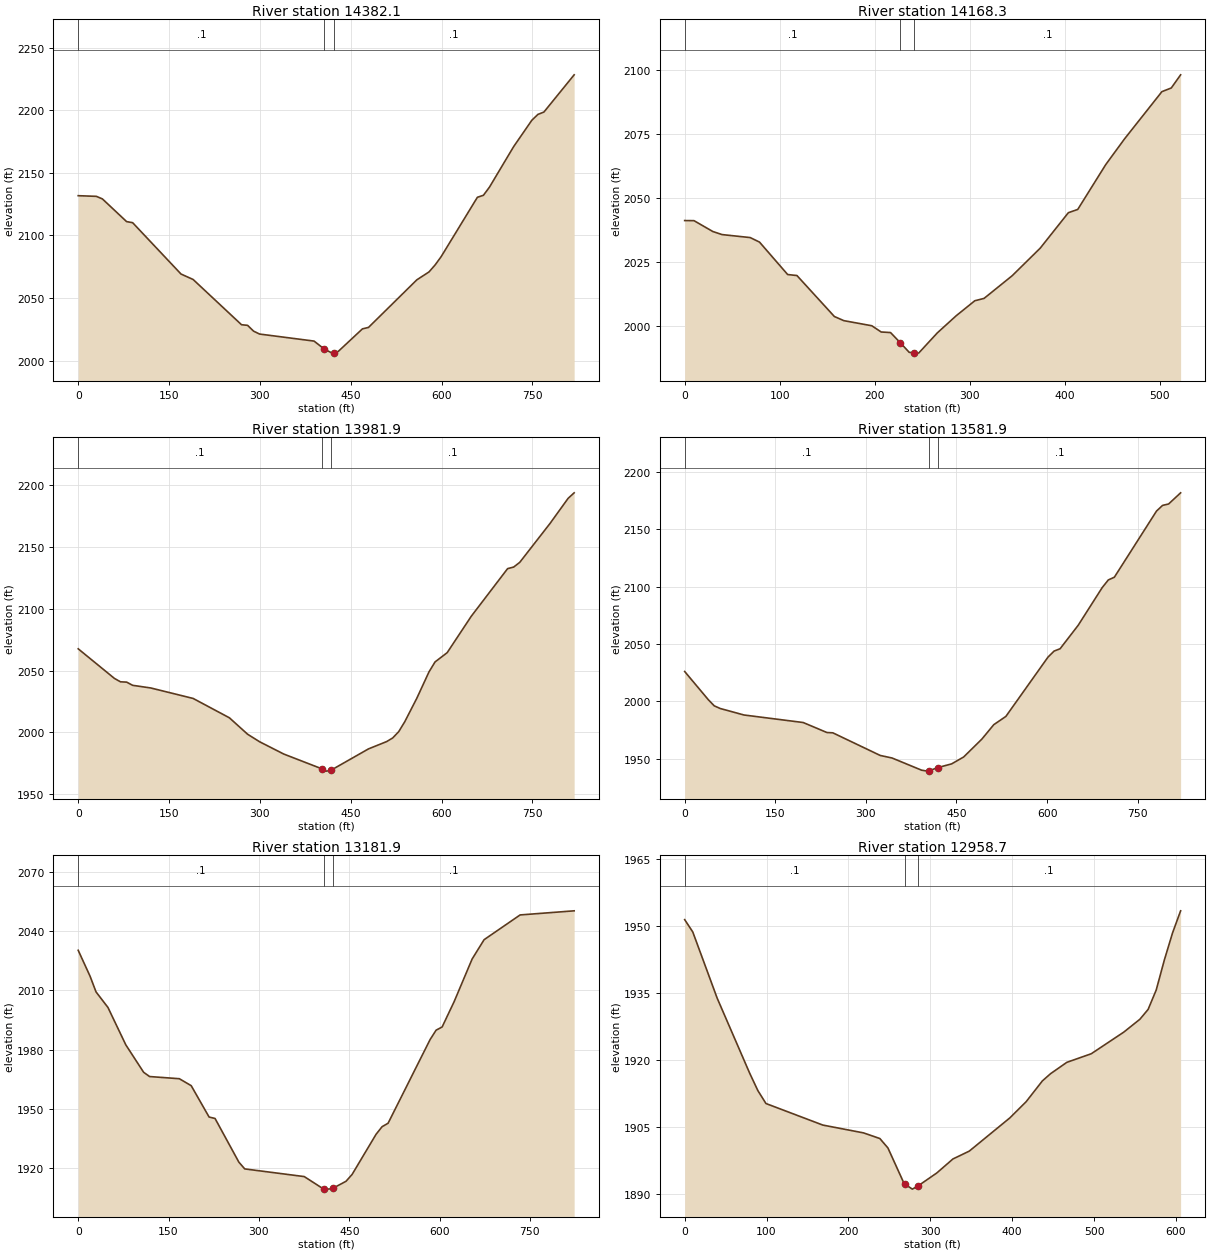
Type RM Length L Ch R = 1 ,14382.1 ,215.5,213.8,212
XS GIS Cut Line= 3
     1981519.326      284467.284     1981385.197      284080.374
     1981251.067      283693.464
#Sta/Elev= 30
       0 2131.71      30 2131.19      40 2129.12    79.9 2111.01    89.9 2110.13
   169.8  2069.1   189.8 2064.74   269.7 2028.59   279.7 2028.11   289.6 2023.46
   299.6 2021.14   389.5 2015.52   406.6 2009.05   419.5  2005.9   421.6 2006.19
   429.5 2007.29   469.4  2025.3   479.4 2026.45   559.3 2064.51   579.3 2070.78
   589.3 2076.32   599.3 2082.95   659.2 2130.43   669.2 2132.05   679.2 2138.59
   719.1 2170.94   749.1 2191.98   759.1 2196.65   769.1 2198.57     819  2228.3
#Mann= 3 , 0 , 0
       0      .1       0   406.6    .045       0   421.6      .1       0
Bank Sta=406.6,421.6
XS Rating Curve= 0 ,0
Exp/Cntr=0.3,0.1

Type RM Length L Ch R = 1 ,14168.3 ,189.5,186.5,183.4
XS GIS Cut Line= 2
     1981675.537      284213.415     1981466.788      283734.853
#Sta/Elev= 30
       0 2041.04     9.8    2041    29.6 2036.77    39.4 2035.56      69 2034.39
    78.8 2032.62   108.4 2019.96   118.2 2019.56   157.6 2003.56   167.5 2001.95
     197 1999.95   206.9 1997.51   216.7  1997.3   226.9 1993.36   236.4 1989.56
   241.9 1989.39   246.3 1989.26     266 1997.18   285.7 2003.81   305.4 2009.71
   315.2 2010.64   344.8  2019.5   374.3 2030.26   403.9  2044.1   413.8 2045.39
   443.3 2062.91     463 2072.91   502.4 2091.39   512.3 2092.83   522.1 2097.96
#Mann= 3 , 0 , 0
       0      .1       0   226.9    .045       0   241.9      .1       0
Bank Sta=226.9,241.9
XS Rating Curve= 0 ,0
Exp/Cntr=0.3,0.1

Type RM Length L Ch R = 1 ,13981.9 ,391,400,411.3
XS GIS Cut Line= 3
     1981958.413      284260.474     1981745.424      283910.723
     1981532.434      283560.972
#Sta/Elev= 30
       0 2067.61    59.9 2043.65    69.9 2040.92    79.9  2040.7    89.9 2038.11
   119.8 2035.96   189.8 2027.49   249.7 2011.84   279.7 1998.58   299.6 1992.47
   339.6 1982.52     402 1970.68   409.5 1968.74     417 1969.35   479.4 1986.72
   509.4 1992.63   519.4 1995.57   529.4 2000.73   539.3 2008.69   559.3 2027.77
   579.3 2048.96   589.3 2057.02   609.3 2064.49   649.2    2094   709.1 2132.42
   719.1  2133.7   729.1 2137.47     779 2168.85     809 2189.22     819 2193.71
#Mann= 3 , 0 , 0
       0      .1       0     402    .045       0     417      .1       0
Bank Sta=402,417
XS Rating Curve= 0 ,0
Exp/Cntr=0.3,0.1

Type RM Length L Ch R = 1 ,13581.9 ,392.4,399.9,400.6
XS GIS Cut Line= 3
     1982173.695      284166.631       1982112.6      283759.132
     1982093.102      283350.548
#Sta/Elev= 30
       0 2026.01    39.2 2001.35      49 1996.03    58.9 1993.72    98.1 1988.06
   196.2 1981.49   235.5 1972.77   245.3 1972.49   323.8 1952.74   343.4 1950.52
   392.4 1939.86   402.2 1939.07   404.6 1939.36   419.6 1942.22     442  1945.4
   461.9 1951.41   491.9 1966.94   511.8 1979.62   531.8 1986.82   601.6 2038.62
   611.6 2043.81   621.6 2045.89   651.5 2066.32   691.4 2099.32   701.4 2105.91
   711.4 2108.29   781.2 2166.01   791.2 2170.95   801.2 2172.19   821.1 2181.93
#Mann= 3 , 0 , 0
       0      .1       0   404.6    .045       0   419.6      .1       0
Bank Sta=404.6,419.6
XS Rating Curve= 0 ,0
Exp/Cntr=0.3,0.1

Type RM Length L Ch R = 1 ,13181.9 ,213.1,223.3,238
XS GIS Cut Line= 3
     1982436.517      284147.637     1982511.129      283739.594
     1982502.038      283331.123
#Sta/Elev= 30
       0 2030.28    19.8  2017.1    29.6 2009.25    49.4 2001.38      79  1982.5
   108.6 1968.62   118.5 1966.46   167.9 1965.36   187.6 1961.84   217.3 1945.99
   227.2 1945.26   266.7  1923.2   276.5 1919.76   375.3 1915.88   407.3 1909.61
   414.8 1909.54   422.3 1909.88   444.7 1913.52   454.7 1916.95   494.5 1937.24
   504.5  1941.1   514.5 1942.86   584.2 1985.13   594.2  1989.9   604.2 1991.52
   624.1 2004.29     654 2025.87   673.9 2035.65   733.7 2048.16   823.4 2050.24
#Mann= 3 , 0 , 0
       0      .1       0   407.3    .045       0   422.3      .1       0
Bank Sta=407.3,422.3
XS Rating Curve= 0 ,0
Exp/Cntr=0.3,0.1

Type RM Length L Ch R = 1 ,12958.7 ,178.7,176.5,174.7
XS GIS Cut Line= 2
     1982555.978      284016.026     1982898.213      283516.163
#Sta/Elev= 30
       0 1951.43     9.9 1948.66    39.7 1933.83    79.4 1917.02    89.4 1913.12
    99.3 1910.22   168.8 1905.39   218.5 1903.64   238.4 1902.38   248.3 1900.26
   268.1 1892.26   269.5 1892.09   278.1 1891.04   284.5 1891.69   307.9 1894.65
   327.7  1897.8   347.6 1899.55   397.2    1907   417.1 1910.63     437  1915.3
   446.9  1916.9   466.8 1919.45   496.6 1921.37   536.3 1926.21   556.1 1929.11
   566.1 1931.31     576 1935.66   585.9 1942.36   595.9 1948.43   605.8  1953.4
#Mann= 3 , 0 , 0
       0      .1       0   269.5    .045       0   284.5      .1       0
Bank Sta=269.5,284.5
XS Rating Curve= 0 ,0
Exp/Cntr=0.3,0.1

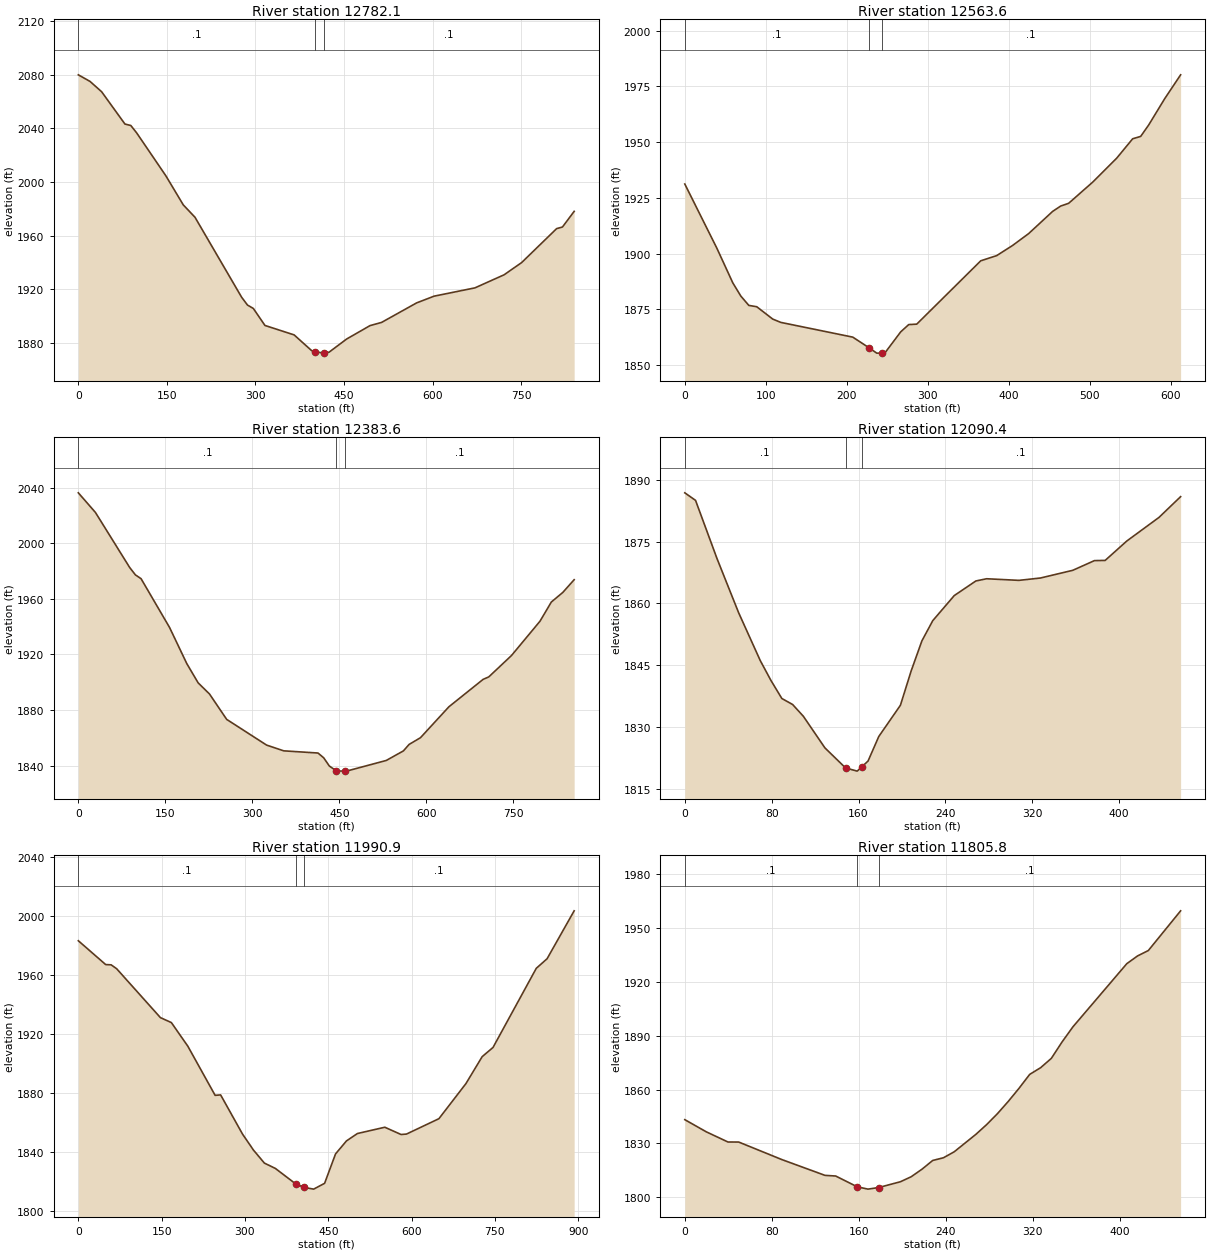
Type RM Length L Ch R = 1 ,12782.1 ,224.1,218.2,211.9
XS GIS Cut Line= 3
     1982641.342      284273.098     1982832.616      283916.053
     1983045.745      283537.181
#Sta/Elev= 30
       0  2079.8    19.8  2074.9    39.5 2067.18      79 2043.12    88.9 2042.06
    98.8 2036.55   148.2 2004.63   177.8  1982.9   197.6 1973.71   276.6 1914.13
   286.5 1908.31   296.4 1905.79   316.1 1893.12   365.5 1886.09   395.2 1874.36
   401.6 1873.64   414.9 1872.51   416.6 1872.64   424.8 1873.24   454.4    1883
     494 1892.99   513.7  1895.4     573 1909.93   602.6 1914.94   671.8 1921.12
   721.2 1930.87   750.8 1939.94   810.1 1965.24     820 1966.46   839.8  1978.1
#Mann= 3 , 0 , 0
       0      .1       0   401.6    .045       0   416.6      .1       0
Bank Sta=401.6,416.6
XS Rating Curve= 0 ,0
Exp/Cntr=0.3,0.1

Type RM Length L Ch R = 1 ,12563.6 ,170.2,180,192
XS GIS Cut Line= 2
     1982991.938      284190.694     1983135.364      283595.687
#Sta/Elev= 30
       0 1931.21    39.5 1902.52    59.2 1886.96    69.1 1881.03      79 1876.82
    88.8 1876.22   108.6 1870.67   118.5  1869.2   207.3  1862.6   227.8 1857.74
   236.9 1855.43   242.8 1855.43   246.8 1855.43   266.5 1864.96   276.4 1868.22
   286.3 1868.42   365.3  1896.8     385 1899.13   404.7  1903.7   424.5 1909.02
   454.1 1918.96     464 1921.34   473.8 1922.57   503.5 1932.06   533.1 1942.79
   552.8 1951.48   562.7 1952.55   572.6 1957.67   592.3 1969.42     612 1980.14
#Mann= 3 , 0 , 0
       0      .1       0   227.8    .045       0   242.8      .1       0
Bank Sta=227.8,242.8
XS Rating Curve= 0 ,0
Exp/Cntr=0.3,0.1

Type RM Length L Ch R = 1 ,12383.6 ,305,292.9,278.7
XS GIS Cut Line= 3
     1982939.192      284368.496     1983216.449      284010.893
     1983491.531      283717.191
#Sta/Elev= 30
       0 2036.27    29.5 2022.15    88.5 1982.58    98.4 1977.26   108.2  1974.5
   157.4 1939.35   186.9 1913.53   206.6 1899.58   226.2 1891.56   255.8 1873.31
   324.6 1854.83   354.1 1850.69   413.2 1849.12     423 1845.71   432.8 1839.78
     445 1836.21     460 1836.11   462.3  1836.1     531 1843.78   560.5 1850.65
   570.3  1855.3   589.9 1860.13     639  1882.4   697.9 1902.09   707.7 1903.88
   746.9 1919.27     796 1943.93   815.6 1957.75   835.3 1964.62   854.9 1973.78
#Mann= 3 , 0 , 0
       0      .1       0     445    .045       0     460      .1       0
Bank Sta=445,460
XS Rating Curve= 0 ,0
Exp/Cntr=0.3,0.1

Type RM Length L Ch R = 1 ,12090.4 ,108.2,99.5,90.8
XS GIS Cut Line= 2
     1983363.995      284385.243     1983432.158      283933.662
#Sta/Elev= 30
       0 1886.82     9.9 1884.99    29.8 1870.78    49.6 1857.72    69.5 1846.12
    79.4 1841.27    89.4 1836.91    99.3 1835.46   109.2  1832.6   129.1 1824.92
   148.1 1820.06   158.8 1819.29   163.1 1820.34   168.8 1821.74   178.7  1827.7
   198.6 1835.27   208.5  1843.6   218.4  1850.9   228.4  1855.8   248.2 1861.89
   268.1 1865.43     278 1865.97   307.8 1865.58   327.6 1866.15   357.4 1868.02
   377.3 1870.37   387.2 1870.42   407.1 1875.12   436.8 1880.86   456.7 1885.89
#Mann= 3 , 0 , 0
       0      .1       0   148.1    .045       0   163.1      .1       0
Bank Sta=148.1,163.1
XS Rating Curve= 0 ,0
Exp/Cntr=0.3,0.1

Type RM Length L Ch R = 1 ,11990.9 ,177.1,184.9,192.7
XS GIS Cut Line= 3
     1983573.969      284623.113     1983449.199      284085.609
     1983587.522      283774.066
#Sta/Elev= 30
       0 1983.25    49.3 1967.11    59.1 1966.94      69  1964.3   147.8  1931.2
   167.5 1927.85   197.1 1911.88   246.3 1878.57   256.2 1878.88   295.6 1852.36
   315.3 1841.53     335  1832.7   354.7 1829.11   391.6 1818.55   406.6 1816.23
   423.7 1815.08   443.4 1819.01   463.1 1838.92   482.8 1847.73   502.5 1852.73
   551.8 1856.98     581 1852.07   590.8 1852.35   649.2 1862.77   697.9 1886.55
   727.1 1904.78   746.6 1910.99   824.5 1964.58     844 1971.08   892.7 2003.51
#Mann= 3 , 0 , 0
       0      .1       0   391.6    .045       0   406.6      .1       0
Bank Sta=391.6,406.6
XS Rating Curve= 0 ,0
Exp/Cntr=0.3,0.1

Type RM Length L Ch R = 1 ,11805.8 ,215.6,222.4,229.9
XS GIS Cut Line= 2
     1983638.067        284332.7      1983690.61        283879.7
#Sta/Elev= 30
       0 1843.25    19.8 1836.47    39.7 1830.82    49.6 1830.79    89.2 1821.05
   128.9 1812.26   138.8 1811.88   158.6 1805.88   168.5 1804.59   178.4 1805.49
   198.3  1808.7   208.2 1811.48   218.1 1815.65     228 1820.54   237.9 1822.05
   247.8 1825.38   267.7 1835.07   277.6  1840.5   287.5 1846.56   297.4 1853.34
   307.3 1860.64   317.2 1868.45   327.2 1872.15   337.1 1877.36     347 1886.52
   356.9 1894.87   406.5 1930.06   416.4 1934.37   426.3 1937.37     456 1959.47
#Mann= 3 , 0 , 0
       0      .1       0   158.6    .045       0   178.4      .1       0
Bank Sta=158.6,178.4
XS Rating Curve= 0 ,0
Exp/Cntr=0.3,0.1

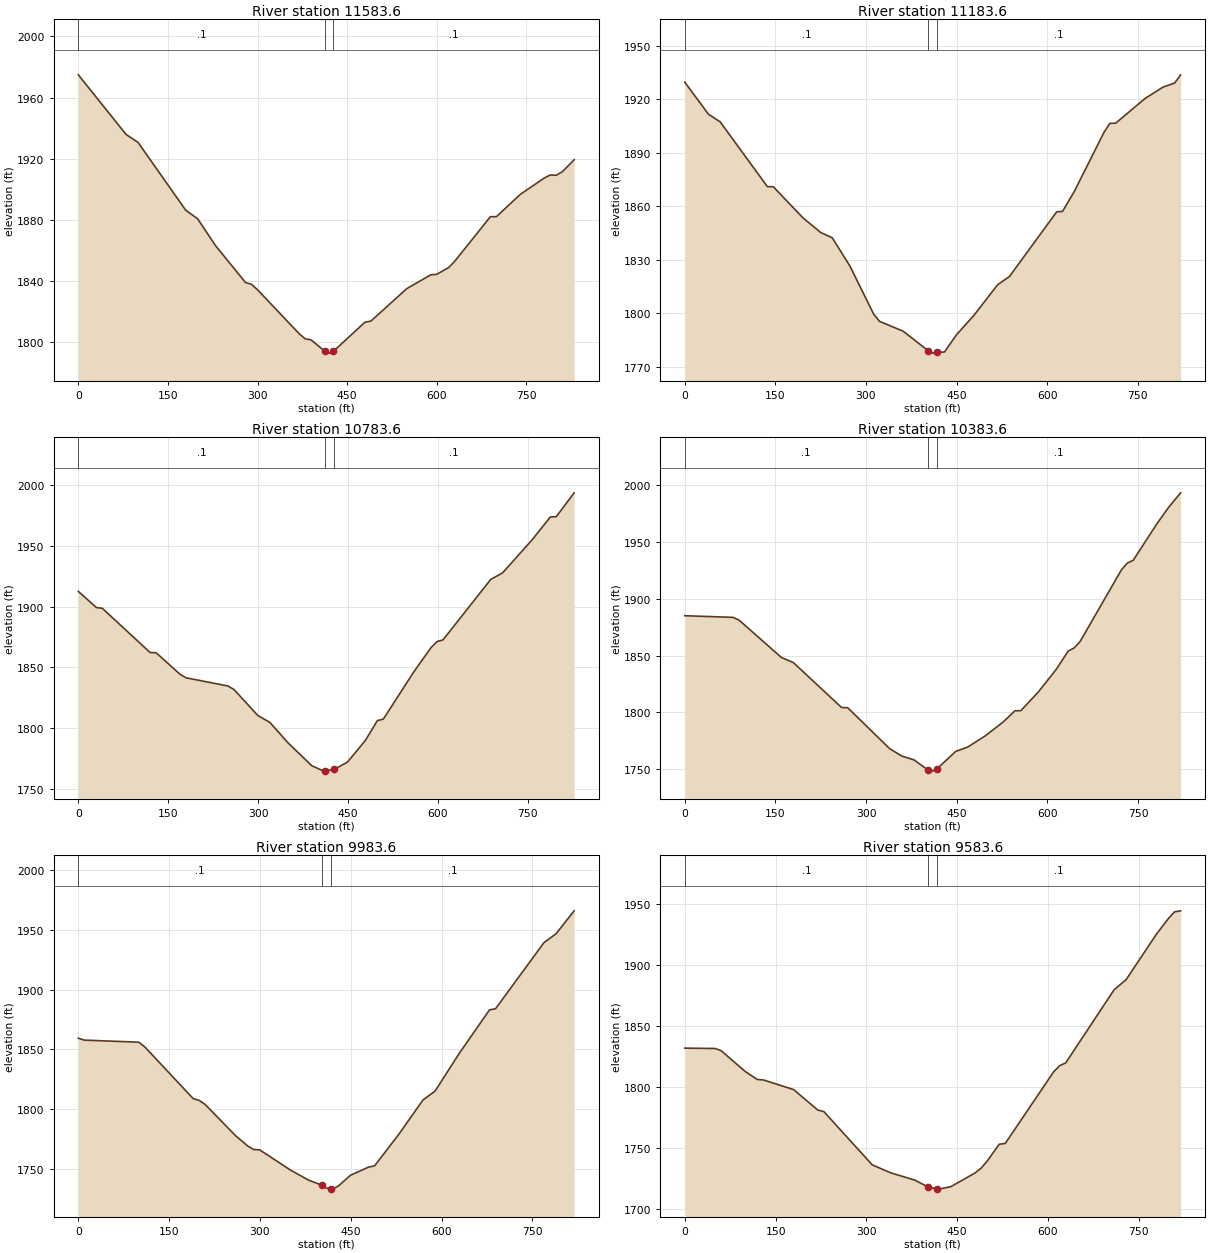
Type RM Length L Ch R = 1 ,11583.6 ,416.5,400,385.3
XS GIS Cut Line= 3
     1983690.334      284640.982     1983859.491      284256.951
     1984037.403      283887.202
#Sta/Elev= 30
       0 1974.88    79.9 1935.87    99.9 1930.67   179.8 1886.27   199.8 1880.61
   229.8 1863.01   279.8 1838.95   289.8 1837.76   299.7 1834.31   369.7  1805.4
   379.7 1802.11   389.7 1801.36   412.1 1794.08   419.6 1792.71   427.1 1793.93
   479.7 1812.94   489.7 1813.66   549.7 1834.89   589.8 1843.95   599.8 1844.29
   619.8 1848.68   629.8  1852.7   689.8 1882.02   699.9 1882.04   739.9 1896.64
   779.9 1907.29   789.9 1909.32   799.9 1909.14     810 1911.36     830 1919.32
#Mann= 3 , 0 , 0
       0      .1       0   412.1    .045       0   427.1      .1       0
Bank Sta=412.1,427.1
XS Rating Curve= 0 ,0
Exp/Cntr=0.3,0.1

Type RM Length L Ch R = 1 ,11183.6 ,389.1,400,412.4
XS GIS Cut Line= 3
     1984347.026      284694.719     1984224.364      284303.025
     1984147.468      283899.753
#Sta/Elev= 30
       0  1929.7    39.1 1911.75    58.6 1907.43   136.8 1871.08   146.6 1871.03
   195.4 1853.67   224.8 1845.42   244.3 1842.34   273.6 1826.44   312.7 1799.58
   322.5 1795.51   361.6 1789.98     403 1779.03   410.4 1777.68     418 1778.06
     430 1778.31   449.6 1787.87   478.9 1798.94     518 1816.06   537.5 1820.64
   615.7 1856.92   625.5 1857.22     645  1868.4   693.9 1901.42   703.7 1906.57
   713.5  1906.7   762.3 1920.61   791.7 1926.91   811.2 1929.25     821 1933.83
#Mann= 3 , 0 , 0
       0      .1       0     403    .045       0     418      .1       0
Bank Sta=403,418
XS Rating Curve= 0 ,0
Exp/Cntr=0.3,0.1

Type RM Length L Ch R = 1 ,10783.6 ,409.7,400,388.2
XS GIS Cut Line= 3
     1984544.231      284681.935     1984616.225      284268.856
     1984755.577      283885.637
#Sta/Elev= 30
       0 1912.61      30 1899.32    39.9 1898.71   119.8 1862.17   129.8 1862.02
   169.7 1844.25   179.7 1841.35   249.6 1834.62   259.6 1831.73   299.5 1810.26
   319.5 1804.62   349.4 1787.94   389.4  1768.9   409.3 1764.42   411.8 1764.51
   426.8 1765.81   449.1 1771.94     479 1789.86   498.9  1806.1   508.8  1807.3
   558.5 1845.43   588.4  1866.3   598.3 1871.17   608.3 1872.61   687.8 1922.39
   707.7 1927.89   757.5 1955.41   787.3 1973.94   797.2 1974.18   827.1 1993.86
#Mann= 3 , 0 , 0
       0      .1       0   411.8    .045       0   426.8      .1       0
Bank Sta=411.8,426.8
XS Rating Curve= 0 ,0
Exp/Cntr=0.3,0.1

Type RM Length L Ch R = 1 ,10383.6 ,401.7,400,396.4
XS GIS Cut Line= 3
     1985105.031      284724.102     1985001.093       284328.34
     1984930.714       283923.11
#Sta/Elev= 30
       0  1885.2    79.8 1883.77    89.8 1881.34   159.7  1848.5   179.6 1843.93
   259.5 1804.31   269.5 1804.18   339.3 1767.95   359.3 1761.55   379.2 1758.23
   401.7 1749.56   409.2 1748.29   416.7 1749.99   448.4  1765.7   467.9 1769.41
   497.3  1779.4   526.7  1791.5   546.3 1801.42   556.1 1801.57   585.4 1818.24
   614.8 1838.05   634.4 1854.07   644.2 1856.81     654 1862.33   722.6 1925.67
   732.3 1931.58   742.1 1934.11   781.3 1966.25   800.9 1980.87   820.5 1993.48
#Mann= 3 , 0 , 0
       0      .1       0   401.7    .045       0   416.7      .1       0
Bank Sta=401.7,416.7
XS Rating Curve= 0 ,0
Exp/Cntr=0.3,0.1

Type RM Length L Ch R = 1 ,9983.6  ,400.9,400,398.7
XS GIS Cut Line= 3
     1985525.324      284645.763     1985392.648      284258.352
     1985259.973      283870.941
#Sta/Elev= 30
       0 1859.39      10 1857.83    99.9  1856.1   109.9  1852.1   189.8 1808.95
   199.8 1807.46   209.7 1803.97   259.7 1778.04   279.7 1769.44   289.6 1766.48
   299.6 1766.18   349.6 1749.59   379.5 1741.13     402 1736.69   409.5 1734.32
     417 1733.63   419.5  1733.4   429.5    1736   449.4 1744.91   479.4 1751.79
   489.4 1752.86   529.4  1779.2   569.3 1807.87   589.3 1815.28   629.2 1846.76
   679.2  1883.1   689.2 1884.04   769.1 1939.22     789 1946.58     819  1965.8
#Mann= 3 , 0 , 0
       0      .1       0     402    .045       0     417      .1       0
Bank Sta=402,417
XS Rating Curve= 0 ,0
Exp/Cntr=0.3,0.1

Type RM Length L Ch R = 1 ,9583.6  ,393.6,399.8,402.3
XS GIS Cut Line= 3
     1985908.364      284486.492      1985760.92      284104.473
     1985606.635      283725.063
#Sta/Elev= 30
       0  1831.7    49.9  1831.4    59.9 1829.69    99.9 1812.56   119.8 1806.04
   129.8 1805.68   179.8 1797.79   219.7 1781.03   229.7 1779.79   309.6 1736.24
   339.6 1729.78   379.5  1723.8     402 1718.16     417  1716.4   419.5 1716.35
   439.5 1718.36   479.4 1729.55   489.4 1733.45   499.4  1739.2   519.4 1753.06
   529.4 1753.73   609.3 1812.28   619.3 1817.35   629.3 1819.65   709.2 1879.43
   729.2 1887.81   779.1  1924.9   799.1 1937.83   809.1 1943.22   819.1 1944.03
#Mann= 3 , 0 , 0
       0      .1       0     402    .045       0     417      .1       0
Bank Sta=402,417
XS Rating Curve= 0 ,0
Exp/Cntr=0.3,0.1