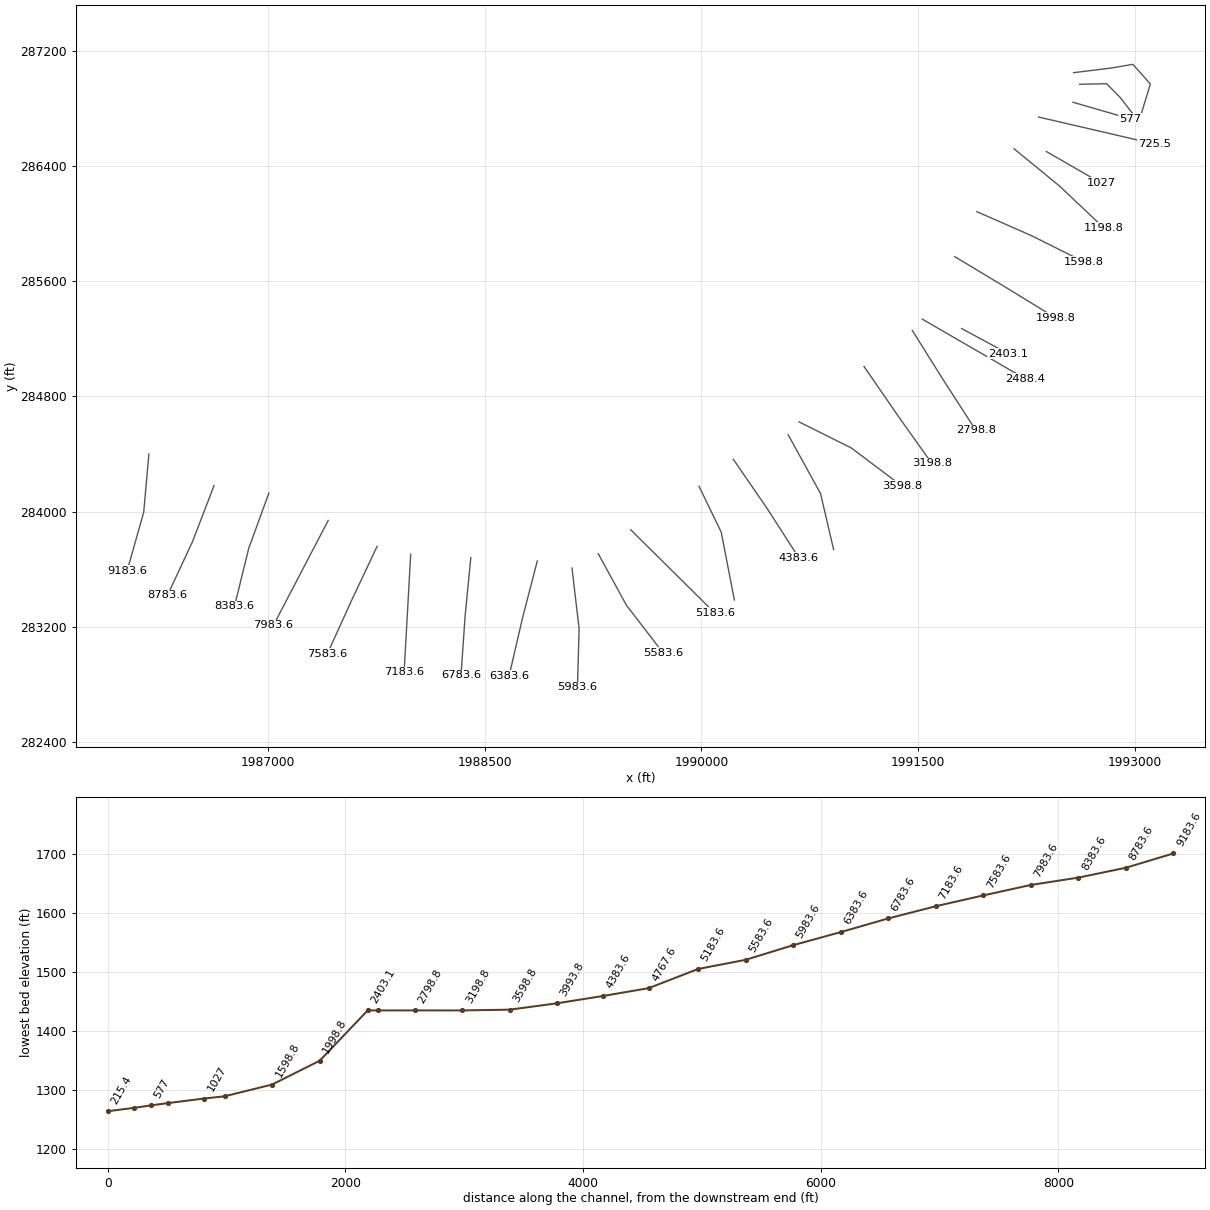
HEC-RAS study FrlyBrnch.prj: FrlyBrnch

--- FrlyBrnch.g01 (geometry) --- (continued)

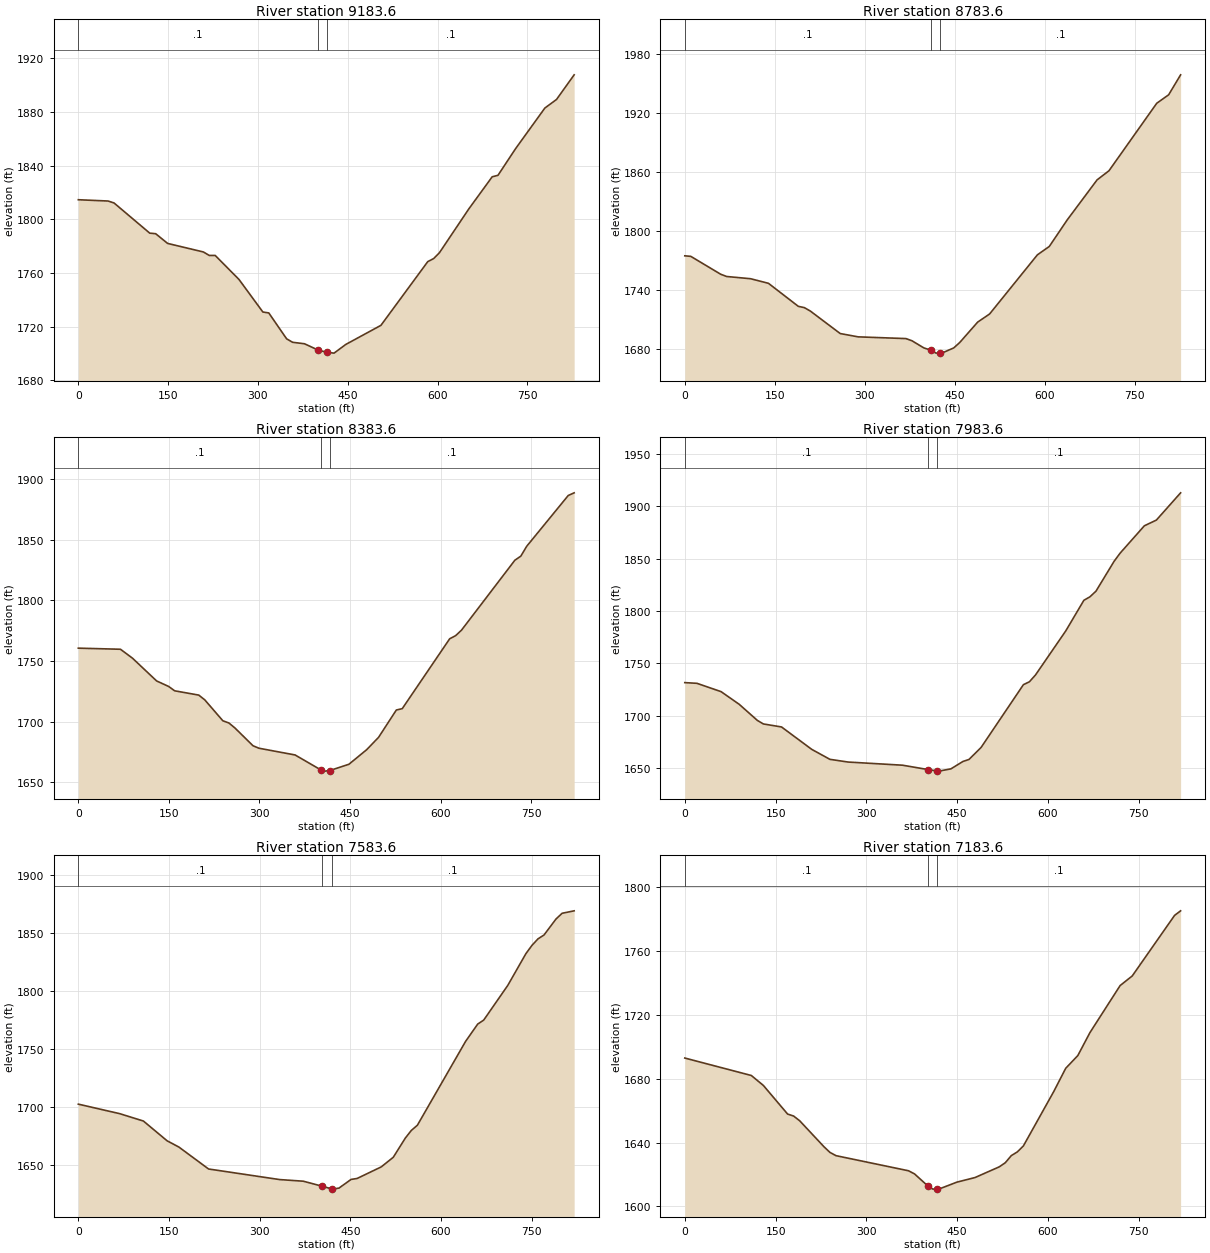
Type RM Length L Ch R = 1 ,9183.6  ,406.3,400.1,396.4
XS GIS Cut Line= 3
     1986175.149      284401.229     1986139.064      283995.271
     1986024.531       283590.67
#Sta/Elev= 30
       0 1814.57    49.7 1813.61    59.6 1812.18   119.3 1789.68   129.2 1789.27
   149.1 1782.04   208.8 1775.68   218.7 1773.09   228.6 1773.09   268.4 1755.17
   308.2 1730.96   318.1 1730.27   347.9 1710.98   357.9 1708.41   377.7 1707.31
   400.1 1702.69   415.1 1700.94   427.1 1700.34   446.7 1706.81   505.4 1721.03
   583.6 1768.47   593.4 1770.74   603.1  1775.1     652 1807.63   691.2 1831.65
   700.9 1832.77   730.3 1852.63   779.2 1882.86   798.7 1889.25   828.1 1907.59
#Mann= 3 , 0 , 0
       0      .1       0   400.1    .045       0   415.1      .1       0
Bank Sta=400.1,415.1
XS Rating Curve= 0 ,0
Exp/Cntr=0.3,0.1

Type RM Length L Ch R = 1 ,8783.6  ,399.6,400,404.5
XS GIS Cut Line= 3
     1986626.153      284182.045     1986476.344      283791.468
     1986304.168      283421.664
#Sta/Elev= 30
       0 1774.74      10  1774.2    59.8 1756.07    69.7 1753.78   109.6 1751.51
   139.4 1746.86   189.2 1723.48   199.2  1722.2   209.2 1718.71     259 1695.89
   288.8 1692.54   368.5 1690.78   378.5 1688.58   398.4  1681.3   410.8 1678.89
   418.3 1676.12   425.8 1676.05   428.3 1676.03   448.2 1681.34   458.1 1686.79
     488 1707.49   507.9 1715.74   587.5 1775.72   607.4 1784.28   637.2 1811.16
     687 1851.79   706.8 1861.04   786.4 1929.51   806.3 1938.14   826.2 1958.37
#Mann= 3 , 0 , 0
       0      .1       0   410.8    .045       0   425.8      .1       0
Bank Sta=410.8,425.8
XS Rating Curve= 0 ,0
Exp/Cntr=0.3,0.1

Type RM Length L Ch R = 1 ,8383.6  ,403,400,394.6
XS GIS Cut Line= 3
     1987005.956      284130.318     1986866.187      283745.955
     1986767.806      283345.453
#Sta/Elev= 30
       0 1760.66    69.8 1759.75    89.8 1752.36   129.7 1733.63   149.6 1729.09
   159.6 1725.51   199.5 1721.97   209.5 1718.04   239.4 1700.82   249.4    1699
   259.4  1694.9   289.3 1680.26   299.3 1678.18   359.1 1672.64   401.5 1660.42
     409 1659.32   416.5 1659.79   448.3 1664.98   477.7    1677   497.4 1687.17
   526.8 1709.67   536.6  1710.8   615.2 1768.38     625 1770.94   634.8  1775.5
   723.2 1833.13     733 1836.46   742.8 1844.62   811.6 1886.46   821.4 1888.66
#Mann= 3 , 0 , 0
       0      .1       0   401.5    .045       0   416.5      .1       0
Bank Sta=401.5,416.5
XS Rating Curve= 0 ,0
Exp/Cntr=0.3,0.1

Type RM Length L Ch R = 1 ,7983.6  ,399.1,400,401.2
XS GIS Cut Line= 3
     1987416.452      283940.051     1987227.136       283576.94
     1987037.821      283213.828
#Sta/Elev= 30
       0 1731.44      20 1730.78    59.9 1722.83    89.9 1710.71   119.8 1695.36
   129.8 1691.95   159.8 1689.06   209.7 1667.65   239.7 1658.13   269.7 1655.54
   359.6 1652.52     402 1648.34     417 1647.02   419.5 1646.86   439.5    1649
   459.4 1656.08   469.4 1658.01   489.4 1669.47   559.3 1729.46   569.3 1732.27
   579.3 1738.77   629.2 1780.79   659.2 1810.12   669.2 1813.44   679.2 1818.85
   709.1 1847.36   719.1 1855.19   759.1 1881.31     779 1886.79     819 1912.82
#Mann= 3 , 0 , 0
       0      .1       0     402    .045       0     417      .1       0
Bank Sta=402,417
XS Rating Curve= 0 ,0
Exp/Cntr=0.3,0.1

Type RM Length L Ch R = 1 ,7583.6  ,391.3,400,408.3
XS GIS Cut Line= 3
      1987754.66      283759.899     1987579.368      283387.761
     1987410.543      283015.156
#Sta/Elev= 30
       0 1702.29    68.6 1694.08   107.7 1687.74   146.9 1670.73   166.5  1665.3
   215.5 1646.45     333 1637.34   372.2 1635.94   403.9 1631.55   418.9 1629.36
   421.3 1629.11   431.3 1630.02   451.3 1637.47   461.2 1638.27   501.2 1648.26
   521.1 1656.53   541.1 1673.11     551 1679.65     561 1684.13   640.8 1756.36
   660.8 1771.23   670.8 1774.71   710.7 1804.65   740.6 1831.92   750.6 1839.03
   760.6 1844.64   770.5 1847.95   790.5  1861.8   800.5 1866.66   820.4 1868.77
#Mann= 3 , 0 , 0
       0      .1       0   403.9    .045       0   418.9      .1       0
Bank Sta=403.9,418.9
XS Rating Curve= 0 ,0
Exp/Cntr=0.3,0.1

Type RM Length L Ch R = 1 ,7183.6  ,400.9,400,399.7
XS GIS Cut Line= 3
     1987987.355      283705.182     1987964.641      283296.313
     1987941.927      282887.443
#Sta/Elev= 30
       0 1692.97   109.9 1682.03   129.8 1675.79   169.8 1657.87   179.8  1656.6
   189.8 1653.65   229.7 1637.45   239.7 1633.85   249.7 1631.79   369.6 1622.31
   379.5 1620.34     402 1612.62   409.5 1610.87     417 1610.82   419.5 1610.81
   449.4 1615.18   479.4 1618.07   519.4 1624.77   529.4 1627.35   539.3 1631.81
   549.3 1634.14   559.3 1637.91   609.3 1671.88   629.2 1686.54   649.2 1694.52
   669.2 1708.91   719.1 1738.41   739.1 1744.43     809 1782.37     819 1785.24
#Mann= 3 , 0 , 0
       0      .1       0     402    .045       0     417      .1       0
Bank Sta=402,417
XS Rating Curve= 0 ,0
Exp/Cntr=0.3,0.1

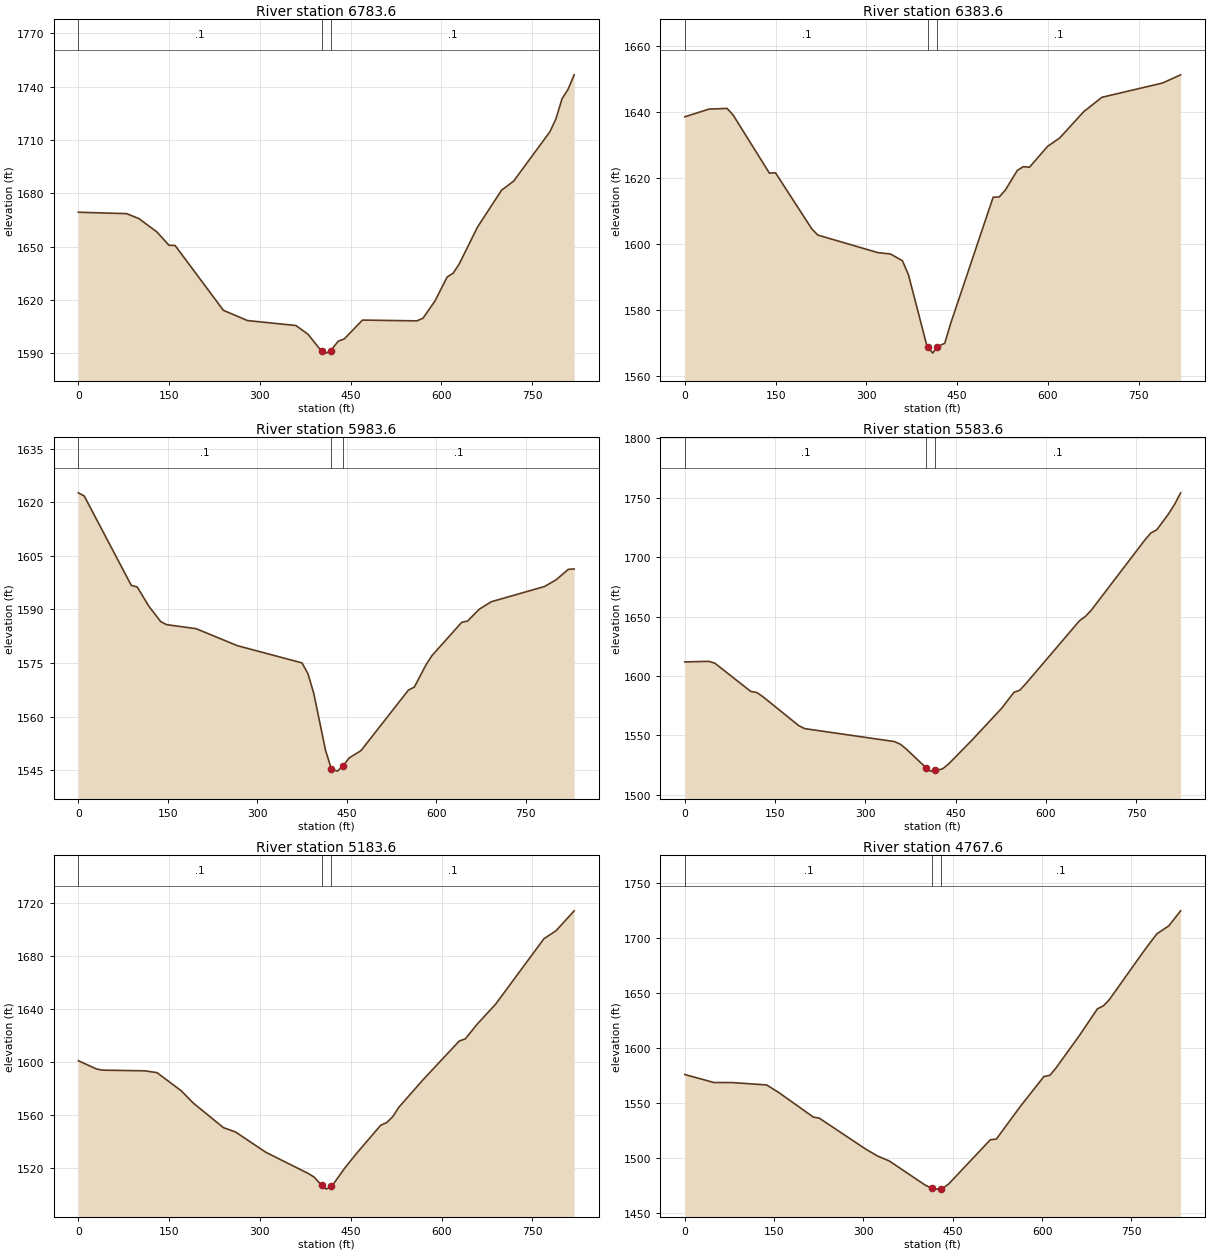
Type RM Length L Ch R = 1 ,6783.6  ,403.5,400,396.4
XS GIS Cut Line= 3
     1988403.564      283682.372     1988363.942      283274.828
      1988335.82      282866.097
#Sta/Elev= 30
       0 1669.39    79.9 1668.59    99.9 1665.84   129.8 1658.31   149.8 1650.79
   159.8 1650.71   239.7 1614.17   279.6  1608.4   359.5 1605.63   379.5 1600.69
     402 1591.14   409.5 1590.08     417 1591.49   429.4 1596.79   439.4 1598.08
   469.4 1608.68   559.4 1608.24   569.4 1609.71   589.3 1619.48   609.3  1632.9
   619.3 1635.08   629.3 1640.26   659.3 1660.91   699.2 1681.79   719.2 1686.89
   779.2 1714.71   789.2 1722.04   799.2 1733.28   809.2 1738.62   819.2 1746.73
#Mann= 3 , 0 , 0
       0      .1       0     402    .045       0     417      .1       0
Bank Sta=402,417
XS Rating Curve= 0 ,0
Exp/Cntr=0.3,0.1

Type RM Length L Ch R = 1 ,6383.6  ,391.6,399.9,404.5
XS GIS Cut Line= 3
     1988863.808      283658.752     1988761.284      283262.324
     1988669.011      282863.184
#Sta/Elev= 30
       0 1638.64      40 1640.98    69.9 1641.19    79.9 1639.17   139.8 1621.54
   149.8 1621.66   209.7 1604.66   219.7 1602.75   319.6 1597.39   339.6 1597.02
   359.5 1594.96   369.5  1590.7   399.5 1569.46     402 1568.82   409.5 1566.92
     417 1568.87   429.4  1569.9   439.4 1576.03   509.4 1614.24   519.4 1614.31
   529.4 1616.37   549.4 1622.39   559.4 1623.51   569.3 1623.32   599.3 1629.67
   619.3 1632.21   659.3 1640.25   689.2 1644.57   789.2 1648.89   819.1 1651.38
#Mann= 3 , 0 , 0
       0      .1       0     402    .045       0     417      .1       0
Bank Sta=402,417
XS Rating Curve= 0 ,0
Exp/Cntr=0.3,0.1

Type RM Length L Ch R = 1 ,5983.6  ,390.9,400.1,416
XS GIS Cut Line= 3
     1989104.003      283610.155     1989153.267      283188.797
     1989141.862      282782.056
#Sta/Elev= 30
       0 1622.61     9.9 1621.73    88.8 1596.71    98.7 1596.28   118.4 1590.85
   138.1 1586.59     148 1585.74   197.3 1584.62   266.4 1579.87   374.9 1575.04
   384.8 1572.07   394.6 1566.55   414.4 1550.56   424.2 1545.35   434.2 1544.77
   444.1 1546.29     454 1548.46   473.8 1550.51   553.2 1567.41   563.2 1568.28
     583 1574.58   592.9 1577.11   642.6 1586.38   652.5 1586.76   672.3 1590.09
   692.2 1592.15   781.5 1596.41   801.4 1598.35   821.2  1601.2   831.1 1601.32
#Mann= 3 , 0 , 0
       0      .1       0   424.2    .045       0   444.1      .1       0
Bank Sta=424.2,444.1
XS Rating Curve= 0 ,0
Exp/Cntr=0.3,0.1

Type RM Length L Ch R = 1 ,5583.6  ,393.4,400,403
XS GIS Cut Line= 3
     1989285.729       283709.52     1989481.303      283350.967
      1989734.56      283021.439
#Sta/Elev= 30
       0 1611.82    39.8 1612.31    49.8 1610.81   109.6 1587.03   119.5 1586.13
   129.5 1582.71   189.3 1558.28   199.2 1555.73   348.6 1544.82   358.6  1542.5
   368.6 1538.32   400.9  1522.8   408.4 1519.97   415.9 1520.52   428.2 1521.84
   438.1 1525.83   477.7 1546.26   527.2 1573.19     547 1586.26   556.8 1588.08
   566.8 1593.54   655.8 1646.39   665.7 1650.04   675.6 1655.37   764.7 1714.46
   774.6 1720.29   784.4 1722.97   804.2 1736.52   814.1 1744.41     824 1754.04
#Mann= 3 , 0 , 0
       0      .1       0   400.9    .045       0   415.9      .1       0
Bank Sta=400.9,415.9
XS Rating Curve= 0 ,0
Exp/Cntr=0.3,0.1

Type RM Length L Ch R = 1 ,5183.6  ,429.9,416,402.1
XS GIS Cut Line= 3
     1989511.048      283875.016     1989801.691      283586.542
     1990092.333      283298.068
#Sta/Elev= 30
       0 1601.33      30 1595.08      40 1594.22   109.9 1593.69   129.8 1592.35
   169.8 1578.72   189.8  1569.4   239.7 1550.84   259.7 1547.54   309.6 1532.27
   379.5 1516.31   389.5 1513.53     402 1507.24   409.5 1504.43     417 1506.45
   419.5 1507.12   439.5 1519.96   459.4 1531.31   499.4 1552.59   509.4 1554.66
   519.4 1559.12   529.4  1566.2   569.3 1586.92   629.2 1616.19   639.2  1617.8
   659.2  1629.1   689.2 1643.95   769.1  1693.4     789  1699.4     819 1714.43
#Mann= 3 , 0 , 0
       0      .1       0     402    .045       0     417      .1       0
Bank Sta=402,417
XS Rating Curve= 0 ,0
Exp/Cntr=0.3,0.1

Type RM Length L Ch R = 1 ,4767.6  ,374.2,384,393.1
XS GIS Cut Line= 3
     1989983.267      284177.205     1990136.994      283858.931
     1990228.098      283388.396
#Sta/Elev= 30
       0 1576.16    49.1 1568.88    78.6 1568.87   137.4  1566.7   157.1 1560.07
     216 1537.42   225.8 1536.53   304.4 1508.11     324 1501.97   343.6 1497.48
   403.4 1475.72   415.3 1472.54   423.4 1471.93   430.3 1472.47   433.3  1472.7
   443.3  1476.7   513.2 1516.87   523.2 1517.43   563.1 1546.86   603.1 1574.35
   613.1  1575.4     623 1581.83     663 1611.85   692.9 1635.87   702.9 1638.58
   712.9  1644.2   772.8 1689.82   792.8 1704.14   812.8 1711.36   832.7 1725.04
#Mann= 3 , 0 , 0
       0      .1       0   415.3    .045       0   430.3      .1       0
Bank Sta=415.3,430.3
XS Rating Curve= 0 ,0
Exp/Cntr=0.3,0.1

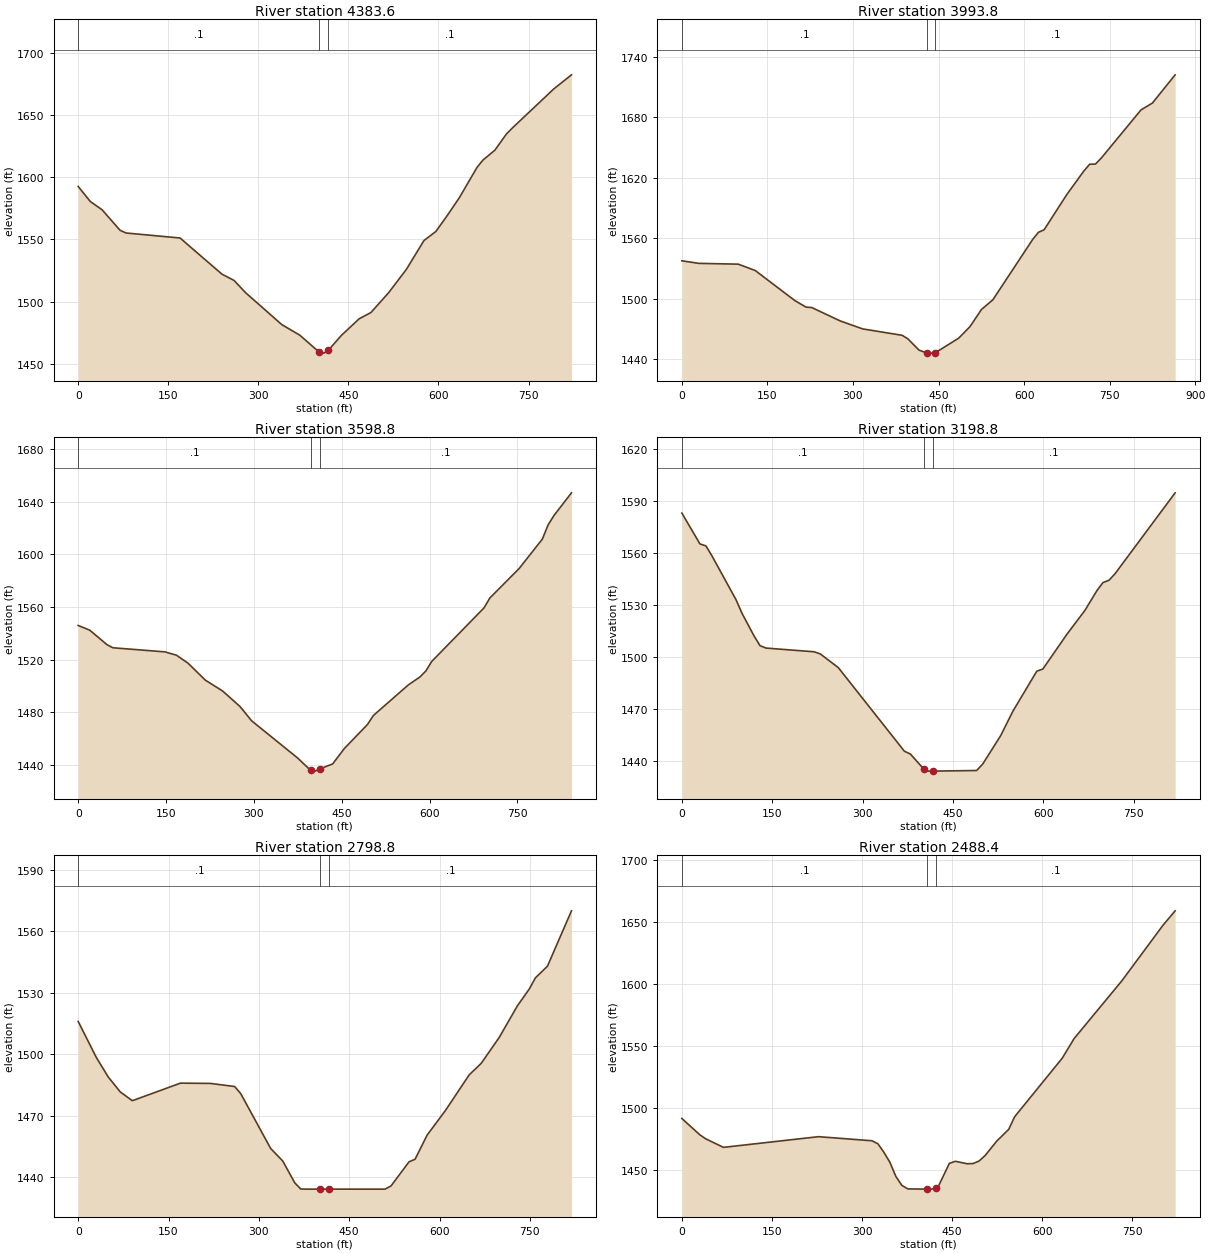
Type RM Length L Ch R = 1 ,4383.6  ,392.1,389.7,388
XS GIS Cut Line= 3
     1990220.862      284364.052     1990452.303      284026.867
     1990675.086      283679.723
#Sta/Elev= 30
       0 1592.63      20 1580.62    39.9 1573.83    69.8 1557.36    79.8 1555.22
   169.6 1551.21   239.4 1522.14   259.4 1517.16   279.3 1507.01   339.2 1481.56
   369.1  1473.1   401.5 1459.43     409 1458.68   416.5 1460.91   438.4 1472.98
   467.9 1486.27   487.5 1491.31     517 1507.24   546.5 1525.97   575.9 1549.21
   595.6 1556.42   615.2 1569.66   634.9  1583.7   664.3 1608.02   674.1 1613.84
   693.8 1621.73   713.4 1634.91   723.2 1639.68     792    1671   821.5 1682.34
#Mann= 3 , 0 , 0
       0      .1       0   401.5    .045       0   416.5      .1       0
Bank Sta=401.5,416.5
XS Rating Curve= 0 ,0
Exp/Cntr=0.3,0.1

Type RM Length L Ch R = 1 ,3993.8  ,381.2,395,404.7
XS GIS Cut Line= 3
      1990600.45      284534.464     1990824.525      284126.565
     1990915.245       283737.49
#Sta/Elev= 30
       0 1537.71    29.7 1535.18      99 1534.38   128.7 1528.06     198 1498.31
   217.8 1491.78   227.8 1491.36   277.3 1478.18   316.9  1470.2   386.2 1463.85
   396.1 1460.43   415.9 1449.15   429.6 1446.29   435.7 1446.17   444.6 1446.62
   485.4 1461.02   505.3 1472.51   525.3 1489.43   545.3 1499.05   615.2 1558.97
   625.2 1565.97   635.2  1568.5   675.1 1603.53   705.1 1626.95   715.1 1633.46
   725.1 1633.59   735.1 1639.37     805 1687.32     825  1694.1   864.9 1722.11
#Mann= 3 , 0 , 0
       0      .1       0   429.6    .045       0   444.6      .1       0
Bank Sta=429.6,444.6
XS Rating Curve= 0 ,0
Exp/Cntr=0.3,0.1

Type RM Length L Ch R = 1 ,3598.8  ,411.6,400,392.9
XS GIS Cut Line= 3
     1990676.287      284623.506      1991038.11      284442.594
     1991387.435      284178.937
#Sta/Elev= 30
       0    1546    19.7 1542.45    49.3 1531.37    59.2 1529.08     148 1525.97
   167.7 1523.46   187.5 1517.39   217.1 1504.52   246.7 1496.24   276.3 1484.49
     296 1473.69   374.9 1445.33     397 1436.01   404.5 1435.47     412 1437.07
   434.4 1440.91   454.3 1452.57     494 1470.92     504 1477.69   563.7 1500.92
   583.6 1506.97   593.5 1511.42   603.5 1518.66     693 1559.41   702.9 1566.89
   752.7 1589.15   792.4  1611.5   802.4 1622.42   812.4  1629.5   842.2 1646.66
#Mann= 3 , 0 , 0
       0      .1       0     397    .045       0     412      .1       0
Bank Sta=397,412
XS Rating Curve= 0 ,0
Exp/Cntr=0.3,0.1

Type RM Length L Ch R = 1 ,3198.8  ,401,400,399
XS GIS Cut Line= 3
     1991125.882      285007.719     1991357.745      284670.196
     1991594.593      284336.074
#Sta/Elev= 30
       0  1582.9      30 1565.15      40 1563.98    49.9 1558.28    89.9 1533.01
    99.9 1525.11   119.8 1512.14   129.8 1506.48   139.8 1505.11   219.7 1502.97
   229.7 1501.76   259.7 1493.87   369.5 1445.65   379.5 1444.03     402 1435.27
   409.5 1434.19     417  1434.2   489.4 1434.54   499.4 1438.21   529.4 1454.67
   549.3 1468.52   589.3  1491.8   599.3 1493.01   639.2 1513.01   669.2 1526.82
   689.2 1538.26   699.2 1542.85   709.2  1544.2   719.2 1547.95     819 1594.58
#Mann= 3 , 0 , 0
       0      .1       0     402    .045       0     417      .1       0
Bank Sta=402,417
XS Rating Curve= 0 ,0
Exp/Cntr=0.3,0.1

Type RM Length L Ch R = 1 ,2798.8  ,299.4,310.4,321.2
XS GIS Cut Line= 3
     1991459.933      285257.767     1991676.964      284910.519
      1991898.93      284566.336
#Sta/Elev= 30
       0 1516.07      30 1498.54    49.9 1488.95    69.9 1481.64    89.9 1477.37
   169.8 1485.95   219.7 1485.81   259.7  1484.3   269.7  1480.9   319.6 1454.03
   339.6 1447.94   359.6 1437.26   369.5 1434.26   379.5  1434.2     402  1434.2
     417  1434.2   509.4  1434.2   519.4 1435.76   549.3 1447.54   559.3 1448.79
   579.3 1460.56   609.3 1472.42   649.2    1490   669.2 1495.64   699.2 1508.35
   729.1 1523.64   749.1 1531.99   759.1 1537.35   779.1 1543.04     819 1570.08
#Mann= 3 , 0 , 0
       0      .1       0     402    .045       0     417      .1       0
Bank Sta=402,417
XS Rating Curve= 0 ,0
Exp/Cntr=0.3,0.1

Type RM Length L Ch R = 1 ,2488.4  ,84.5,85.3,86
XS GIS Cut Line= 2
     1991528.571      285336.758     1992239.009      284924.398
#Sta/Elev= 30
       0 1491.26    29.7 1478.18    39.6 1474.86    69.3 1467.93   227.6 1476.56
   316.7 1473.25   326.6 1470.75   336.5 1463.89   346.4 1455.89   356.3 1444.49
   366.2 1437.28   376.1 1434.38     408  1434.2   415.7 1434.19     423 1434.71
   425.6 1434.89   445.4 1454.99   455.3 1456.68     475 1454.71     485 1454.85
   494.8 1456.86   504.7 1461.19   524.5 1473.07   544.3 1482.49   554.2 1492.69
   633.4 1539.96   653.2 1555.83   732.4 1602.29   801.6 1647.62   821.4 1658.99
#Mann= 3 , 0 , 0
       0      .1       0     408    .045       0     423      .1       0
Bank Sta=408,423
XS Rating Curve= 0 ,0
Exp/Cntr=0.3,0.1

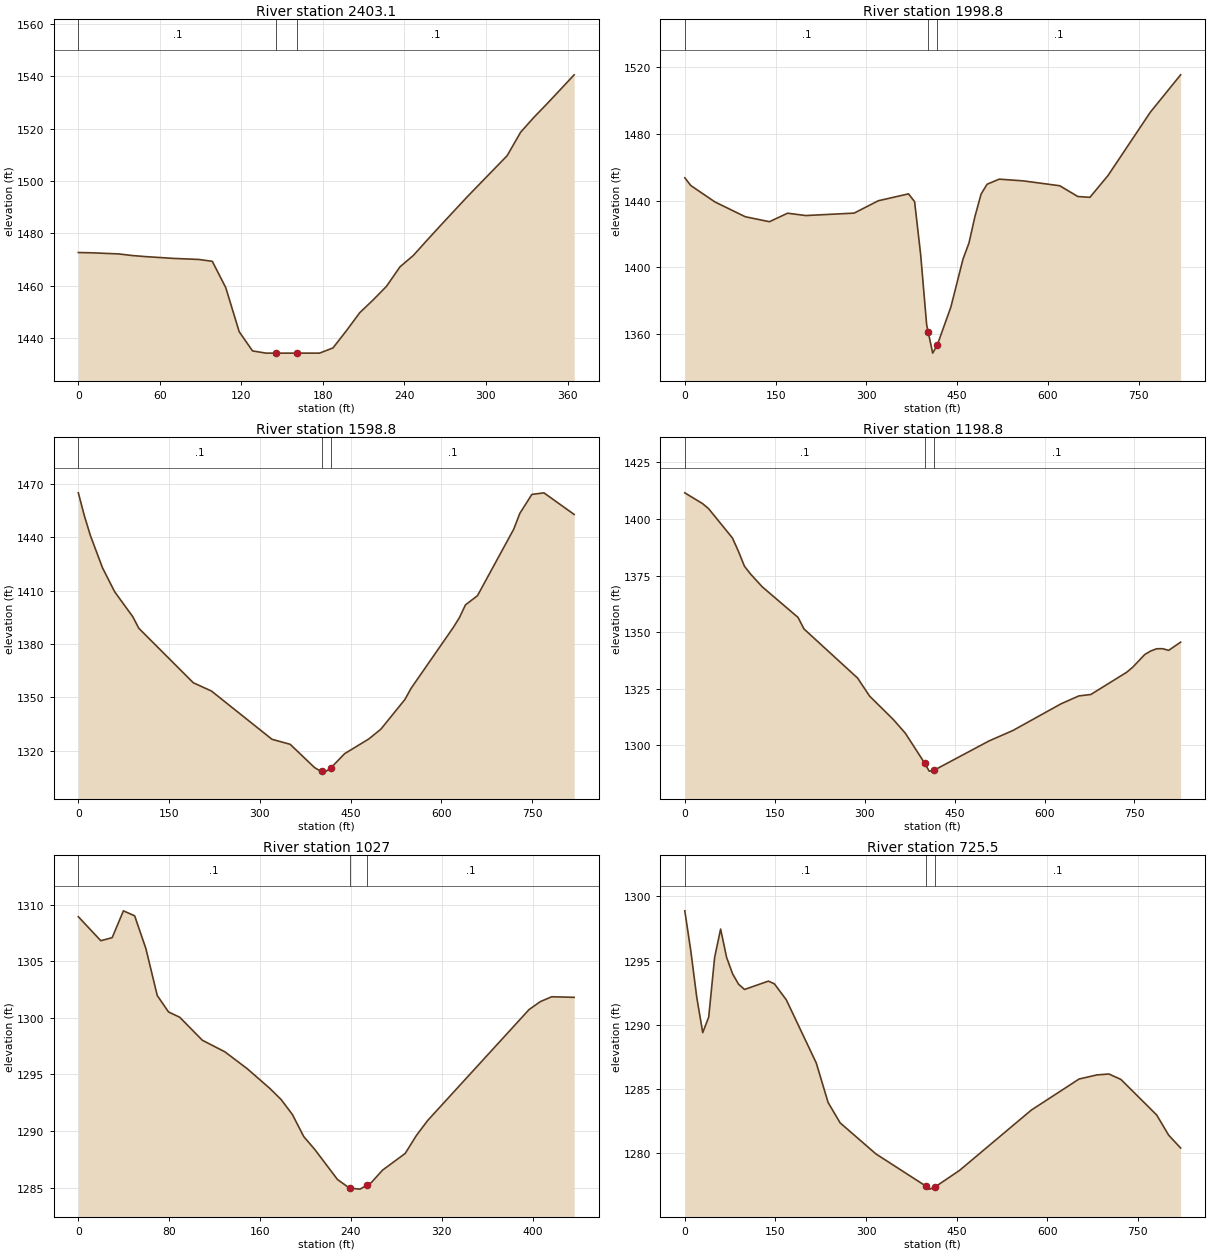
Type RM Length L Ch R = 1 ,2403.1  ,405.5,404.3,402.8
XS GIS Cut Line= 2
     1991801.133      285271.319     1992122.245      285097.982
#Sta/Elev= 30
       0 1472.63     9.9 1472.53    29.6  1472.1    39.4  1471.5    49.3 1471.08
      69 1470.42    88.8 1469.98    98.6 1469.27   108.5 1459.23   118.4 1442.37
   128.2 1435.05   138.1  1434.2   145.6  1434.2   160.6  1434.2   177.5  1434.2
   187.4 1436.18   197.2  1442.7   207.1 1449.64     217 1454.54   226.8 1459.73
   236.7 1467.16   246.6 1471.54   256.4  1477.2   266.3 1482.81     286 1493.81
   315.6 1509.64   325.5 1518.59   335.3 1524.29   345.2  1529.6   364.9 1540.52
#Mann= 3 , 0 , 0
       0      .1       0   145.6    .045       0   160.6      .1       0
Bank Sta=145.6,160.6
XS Rating Curve= 0 ,0
Exp/Cntr=0.3,0.1

Type RM Length L Ch R = 1 ,1998.8  ,397.1,400,402
XS GIS Cut Line= 3
     1991753.915      285769.839     1992104.702      285558.518
     1992453.453      285343.902
#Sta/Elev= 30
       0 1453.56      10 1448.93    49.9 1439.12    99.9 1430.31   139.8 1427.34
   169.8 1432.42   199.8 1431.02   279.7 1432.47   319.6 1439.85   369.6 1443.97
   379.6 1439.29   389.6 1407.69   399.5 1365.78     402 1361.55   409.5 1348.86
     417 1353.69   439.5 1376.39   459.5 1404.97   469.4 1414.63   479.4 1430.63
   489.4 1443.84   499.4 1449.74   519.4 1452.76   559.3 1451.72   619.3 1448.82
   649.2 1442.39   669.2 1441.91   699.2 1454.99   769.1 1492.81     819 1515.06
#Mann= 3 , 0 , 0
       0      .1       0     402    .045       0     417      .1       0
Bank Sta=402,417
XS Rating Curve= 0 ,0
Exp/Cntr=0.3,0.1

Type RM Length L Ch R = 1 ,1598.8  ,406.2,400,393.3
XS GIS Cut Line= 3
     1991906.406      286082.073     1992281.805      285916.963
     1992647.978      285733.877
#Sta/Elev= 30
       0 1465.12      10 1452.16      20 1441.05      40  1422.9      60 1409.49
      90 1395.42     100  1388.9     190 1358.26   220.1 1353.59   320.1 1326.45
   350.1 1323.64   390.1 1310.65   400.1 1308.54   402.6 1308.56   410.1 1308.61
   417.6 1310.42   440.1 1318.35     480 1326.62     500 1332.13   539.9 1348.91
   549.9  1355.1   619.8  1389.4   629.8 1394.87   639.8 1402.05   659.7 1407.25
   719.6 1444.66   729.6 1453.49   749.6 1464.23   769.6  1465.1   819.5 1452.95
#Mann= 3 , 0 , 0
       0      .1       0   402.6    .045       0   417.6      .1       0
Bank Sta=402.6,417.6
XS Rating Curve= 0 ,0
Exp/Cntr=0.3,0.1

Type RM Length L Ch R = 1 ,1198.8  ,167.6,171.4,176.9
XS GIS Cut Line= 3
     1992164.056      286518.292     1992479.113      286259.731
     1992783.621      285971.307
#Sta/Elev= 30
       0 1411.58    29.8 1406.78    39.8 1404.56    79.5 1391.61    89.5 1385.72
    99.4  1379.2   109.4 1375.79   129.2 1370.04   188.9 1356.53   198.8 1351.44
   288.3 1329.72   308.2 1321.78   347.9  1311.4   367.8 1305.39   400.1 1292.14
   407.6 1288.62   415.1 1288.92   507.4 1301.95   547.4 1306.59   627.3 1318.33
   657.2 1321.84   677.2 1322.48   737.1 1332.31   747.1 1334.53   767.1 1340.12
   777.1  1341.7     787 1342.68     797 1342.72     807 1341.98     827  1345.6
#Mann= 3 , 0 , 0
       0      .1       0   400.1    .045       0   415.1      .1       0
Bank Sta=400.1,415.1
XS Rating Curve= 0 ,0
Exp/Cntr=0.3,0.1

Type RM Length L Ch R = 1 ,1027    ,294.6,301.4,308.3
XS GIS Cut Line= 2
     1992388.241      286498.921     1992766.334      286280.586
#Sta/Elev= 30
       0 1308.93    19.8 1306.81    29.8 1307.08    39.7 1309.45    49.6 1309.01
    59.5 1306.11    69.5 1301.97    79.4 1300.52    89.3 1300.05   109.2 1298.02
     129    1297   148.8  1295.5   168.7 1293.76   178.6 1292.78   188.5 1291.46
   198.5 1289.51   208.4 1288.35   228.2 1285.72   238.8 1284.96   248.1 1284.87
   253.8  1285.2     258 1285.45   267.9 1286.55   287.8 1288.02   297.7 1289.61
   307.6 1290.93   396.9 1300.73   406.8 1301.43   416.8 1301.86   436.6 1301.81
#Mann= 3 , 0 , 0
       0      .1       0   238.8    .045       0   253.8      .1       0
Bank Sta=238.8,253.8
XS Rating Curve= 0 ,0
Exp/Cntr=0.3,0.1

Type RM Length L Ch R = 1 ,725.5   ,149.9,148.5,147.1
XS GIS Cut Line= 2
     1992333.948      286738.467      1993133.42      286552.641
#Sta/Elev= 30
       0 1298.87     9.9 1295.77    19.8 1292.14    29.7 1289.39    39.6  1290.6
    49.4 1295.25    59.3 1297.45    69.2 1295.25    79.1 1293.97      89 1293.16
    98.9 1292.75   138.4  1293.4   148.3 1293.19   168.1 1291.94   217.6 1287.03
   237.3 1283.95   257.1 1282.37   316.4 1279.95   399.3 1277.44   405.4 1277.21
   414.3 1277.38   454.9 1278.67   573.6 1283.36   652.7 1285.78   682.3  1286.1
   702.1 1286.17   721.9 1285.75   781.2 1282.98     801 1281.41   820.8 1280.41
#Mann= 3 , 0 , 0
       0      .1       0   399.3    .045       0   414.3      .1       0
Bank Sta=399.3,414.3
XS Rating Curve= 0 ,0
Exp/Cntr=0.3,0.1

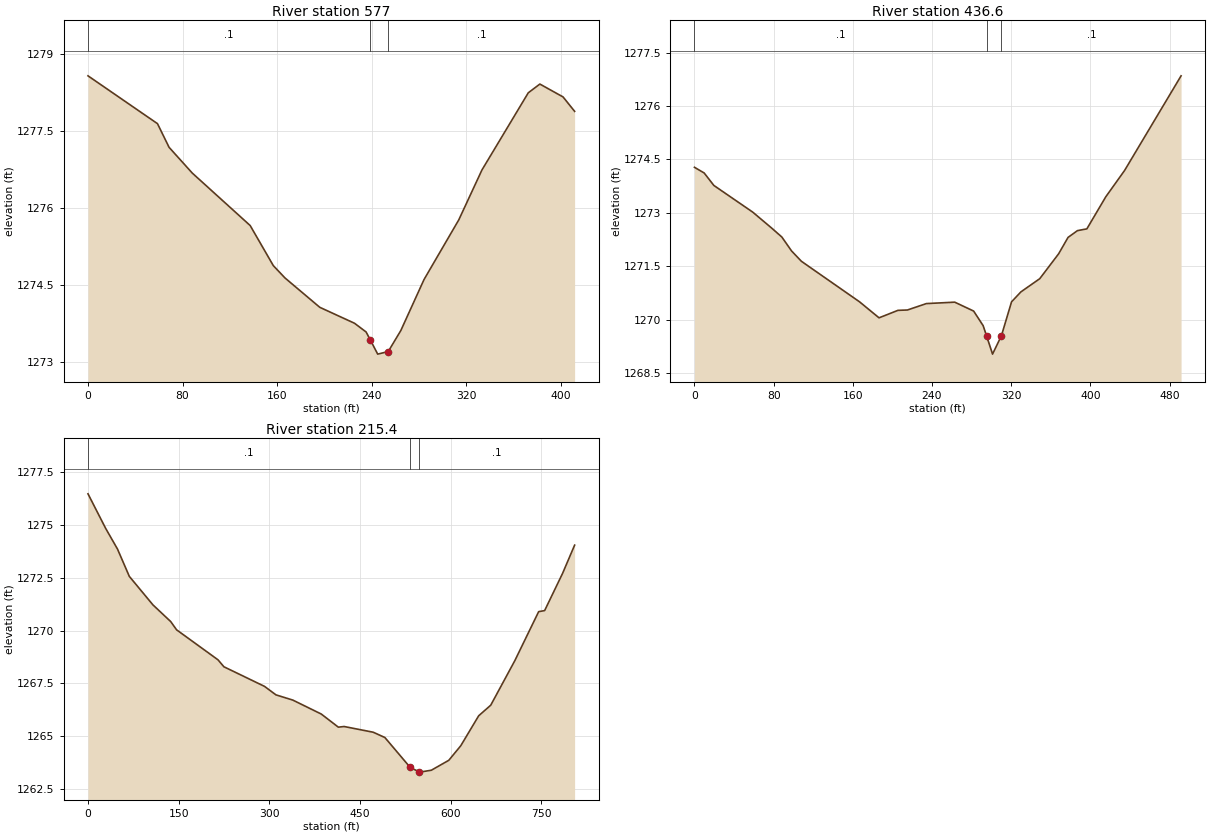
Type RM Length L Ch R = 1 ,577     ,152.1,140.4,128.1
XS GIS Cut Line= 2
     1992572.095      286841.079     1992967.508      286726.282
#Sta/Elev= 21
       0 1278.57    58.8 1277.64    68.6 1277.18    88.2 1276.68   137.2 1275.66
   156.8 1274.88   166.7 1274.64   196.1 1274.07   225.5 1273.76   235.3 1273.59
     239 1273.43   245.1 1273.16     254 1273.21   264.7 1273.62   284.3 1274.61
   313.7 1275.77   333.3 1276.74   372.5 1278.24   382.3 1278.41   401.9 1278.16
   411.7 1277.88
#Mann= 3 , 0 , 0
       0      .1       0     239    .045       0     254      .1       0
Bank Sta=239,254
XS Rating Curve= 0 ,0
Exp/Cntr=0.3,0.1

Type RM Length L Ch R = 1 ,436.6   ,222.4,221.2,220.6
XS GIS Cut Line= 4
      1992618.21      286965.688     1992804.633      286969.613
     1992898.826      286874.439     1993003.811      286739.037
#Sta/Elev= 29
       0 1274.28     9.8 1274.12    19.6 1273.77    58.9 1273.02    78.5 1272.56
    88.3 1272.32    98.1 1271.93     108 1271.64   166.8  1270.5   186.5 1270.05
   205.6 1270.26   215.2 1270.27   234.3 1270.45     263 1270.49   282.1 1270.24
   291.7 1269.83   295.2 1269.54   301.2 1269.03   310.2 1269.55   320.4  1270.5
   329.9 1270.78   348.9 1271.15     368 1271.85   377.5 1272.31     387  1272.5
   396.5 1272.55   415.6 1273.45   434.6 1274.19   491.7 1276.85
#Mann= 3 , 0 , 0
       0      .1       0   295.2    .045       0   310.2      .1       0
Bank Sta=295.2,310.2
XS Rating Curve= 0 ,0
Exp/Cntr=0.3,0.1

Type RM Length L Ch R = 1 ,215.4   ,213.6,215.4,217.1
XS GIS Cut Line= 5
     1992576.019      287046.144     1992837.993      287078.523
      1992986.15      287104.034     1993107.816       286967.65
     1993046.983      286768.472
#Sta/Elev= 30
       0 1276.48    29.3 1274.84    48.9 1273.86    68.4 1272.57   107.5 1271.22
   136.9 1270.43   146.6 1270.04   215.1 1268.62   224.9 1268.29   292.2 1267.36
     311 1266.96   339.1 1266.71   386.1 1266.05   414.3 1265.43   423.9 1265.46
     472 1265.19   491.3 1264.94   533.3 1263.52   548.3 1263.31     549  1263.3
   568.2 1263.39   597.1 1263.86   616.9 1264.55   646.6 1265.97   666.5 1266.47
   706.2 1268.57   745.8  1270.9   755.7 1270.95   785.5 1272.72   805.3 1274.05
#Mann= 3 , 0 , 0
       0      .1       0   533.3    .045       0   548.3      .1       0
Bank Sta=533.3,548.3
XS Rating Curve= 0 ,0
Exp/Cntr=0.3,0.1

Chan Stop Cuts=-1
Use User Specified Reach Order=0
Composite Channel Slope=5